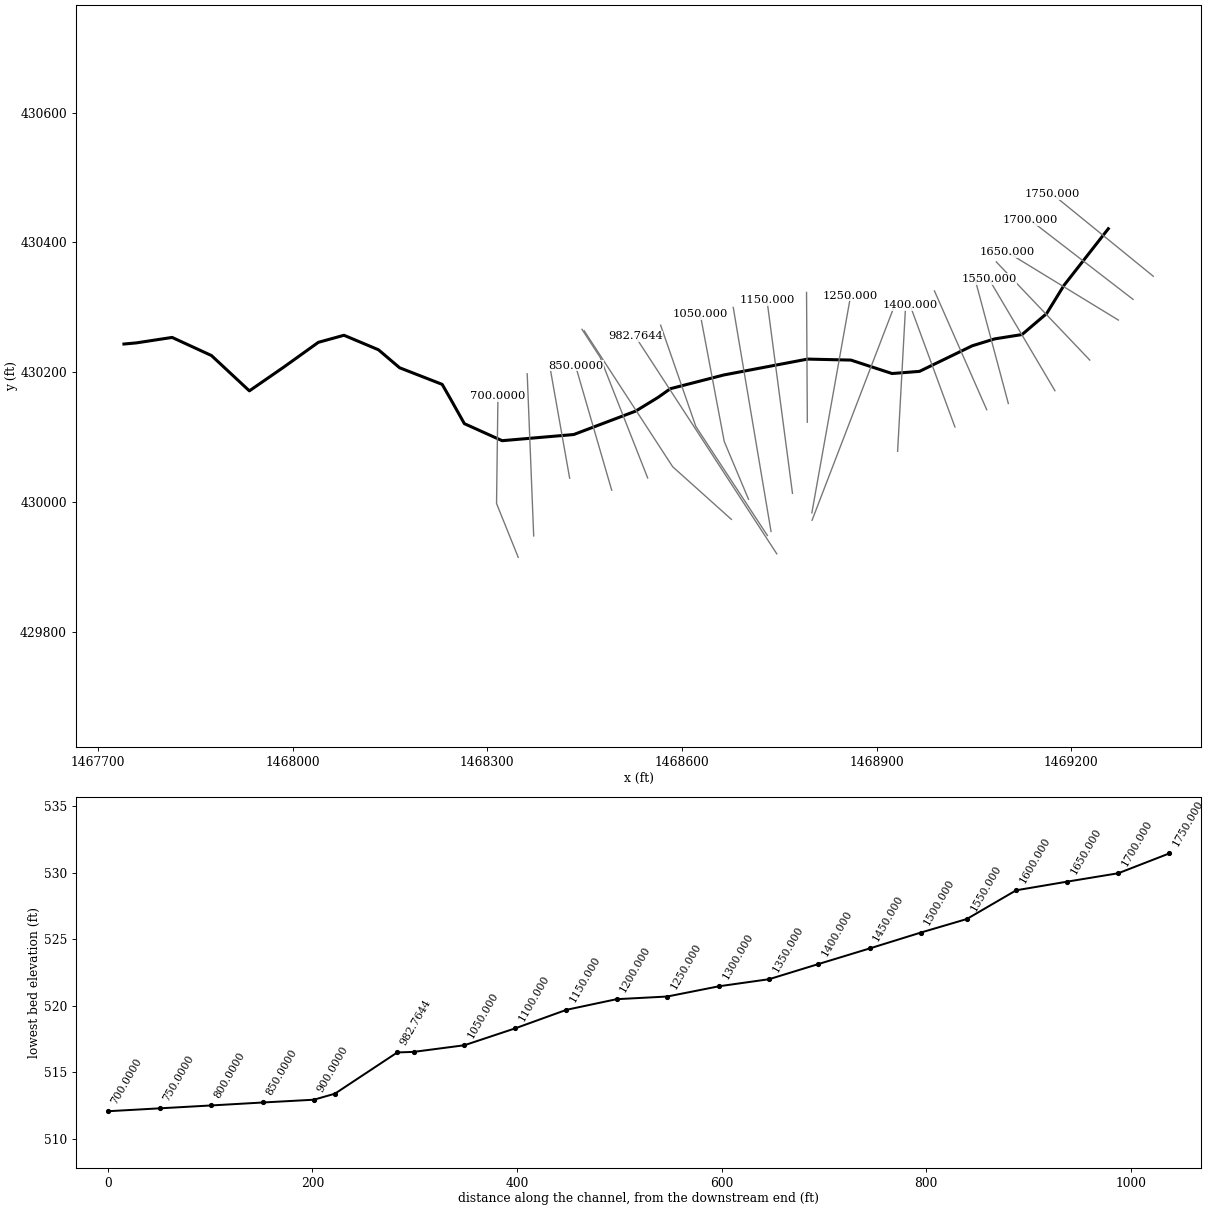
--- CLE-50-2.prj (project) ---

Proj Title=CLE-50-2.25
Current Plan=p19
Default Exp/Contr=0.3,0.1
English Units
Geom File=g01
Geom File=g02
Geom File=g03
Geom File=g04
Geom File=g05
Geom File=g06
Geom File=g07
Geom File=g08
Geom File=g09
Geom File=g10
Geom File=g11
Geom File=g12
Geom File=g13
Geom File=g14
Geom File=g15
Geom File=g16
Geom File=g17
Geom File=g18
Geom File=g19
Flow File=f01
Plan File=p01
Plan File=p02
Plan File=p03
Plan File=p04
Plan File=p05
Plan File=p06
Plan File=p07
Plan File=p08
Plan File=p09
Plan File=p10
Plan File=p11
Plan File=p12
Plan File=p13
Plan File=p14
Plan File=p15
Plan File=p16
Plan File=p17
Plan File=p18
Plan File=p19
Background Map Layer=Bing Satellite
Y Axis Title=Elevation
X Axis Title(PF)=Main Channel Distance
X Axis Title(XS)=Station
BEGIN DESCRIPTION:
US-50 over un-named creek  (CLE-50-2.25). Clermont County, Miami Township.
Downstream portion of channel is in Zone AE of East Fork of Little Miami River. FIRM 39025C0117G Effective March 16, 2006.
Horizontal Coordinate System: NAD 1983 State Plane Ohio South FIPS 3402 Feet
Vertical Datum: NAVD88
END DESCRIPTION:
DSS File=dss
DSS Export Rating Curves= 0
DSS Export Rating Curve Sorted= 0
DSS Export Volume Flow Curves= 0
DXF OffsetX= 0
DXF OffsetY= 0
DXF ScaleX= 1
DXF ScaleY= 10

--- CLE-50-2.p19 (plan) ---

Plan Title=Alternative 1 with Bench Sed Trap Energy
Program Version=6.10
Short Identifier=Alt 1 Bench Sed Trap Energy
Geom File=g19
Flow File=f01
Mixed Flow
K Sum by GR= 0
Std Step Tol= 0.01
Critical Tol= 0.01
Num of Std Step Trials= 20
Max Error Tol= 0.3
Flow Tol Ratio= 0.001
Split Flow NTrial= 30
Split Flow Tol= 0.02
Split Flow Ratio= 0.02
Log Output Level= 0
Friction Slope Method= 1
Unsteady Friction Slope Method= 2
Unsteady Bridges Friction Slope Method= 1
Parabolic Critical Depth
Global Vel Dist= 0 , 0 , 0
Global Log Level= 0
CheckData=True
Encroach Param=-1 ,0,0, 0
BEGIN DESCRIPTION:
*Alternative 1 with 2-Step Channel Pressure Flow
Alternative with rock channel lining and excavation to 513.4 ft at bridge to XS 500. Channel widening from bridge to XS 500. Concrete slab underneath bridge at XS 982. 8-ft bench only on north side of channel at XS 850. Sediment trap at 982. Energy flow calculations for 4% AEP Flood and greater.
END DESCRIPTION:
Computation Interval=1MIN
Output Interval=1HOUR
Instantaneous Interval=1HOUR
Mapping Interval=1HOUR
Computation Time Step Use Courant=        0
Computation Time Step Use Time Series=    0
Computation Time Step Count To Double=0
Computation Time Step Max Doubling=0
Computation Time Step Max Halving=0
Computation Time Step Residence Courant=0
Run HTab= 0
Run UNet= 0
Run Sediment= 0
Run PostProcess= 0
Run WQNet= 0
Run RASMapper= 0
UNET Theta= 1
UNET Theta Warmup= 1
UNET ZTol= 0.02
UNET ZSATol= 0.02
UNET MxIter= 20
UNET Max Iter WO Improvement= 0
UNET MaxInSteps= 0
UNET DtIC= 0
UNET DtMin= 0
UNET MaxCRTS= 20
UNET WFStab= 2
UNET SFStab= 1
UNET WFX= 1
UNET SFX= 1
UNET Gravity=32.174
UNET 1D Methodology=Finite Difference
UNET DSS MLevel= 4
UNET Pardiso=0
UNET DZMax Abort= 100
UNET Use Existing IB Tables=-1
UNET Froude Reduction=False
UNET Froude Limit= 0.8
UNET Froude Power= 4
UNET D1 Cores= 0
UNET WindReference=Eulerian
UNET WindDragFormulation=Hsu (1988)
UNET D2 Coriolis=0
UNET D2 Cores= 0
UNET D2 Theta= 1
UNET D2 Theta Warmup= 1
UNET D2 Z Tol= 0.01
UNET D2 Volume Tol= 0.01
UNET D2 Max Iterations= 20
UNET D2 Equation= 0
UNET D2 RampUpFraction=0.1
UNET D2 TimeSlices= 1
UNET D2 Turbulence Formulation=None
UNET D2 Eddy Viscosity=0.3
UNET D2 Transverse Eddy Viscosity=0.1
UNET D2 Smagorinsky Mixing=0.05
UNET D2 BCVolumeCheck=0
UNET D2 Cores=0
UNET D2 SolverType=PARDISO (Direct)
UNET D2 Minimum Iterations= 2147483647
UNET D2 Maximum Iterations= 2147483647
UNET D2 Restart Number= 10
UNET D2 Relaxation Coeff=1.3
UNET D2 SOR Precondition Iterations= 10
UNET D2 ILUT Maximum Fill= 8
UNET D2 ILUT Tolerance=1E-08
UNET D1D2 MaxIter= 0
UNET D1D2 ZTol=0.01
UNET D1D2 QTol=0.1
UNET D1D2 MinQTol=1
Write IC File= 0
Write IC File at Fixed DateTime=0
Write IC File at Sim End=0
Echo Input=False
Echo Parameters=False
Echo Output=False
Write Detailed= 0
HDF Write Warmup=0
HDF Write Time Slices=0
HDF Flush=0
HDF Compression= 1
HDF Chunk Size= 1
HDF Spatial Parts= 1
HDF Use Max Rows=0
HDF Fixed Rows= 1
Calibration Method= 0
Calibration Iterations= 20
Calibration Max Change=0.05
Calibration Tolerance=0.2
Calibration Maximum=1.5
Calibration Minimum=0.5
Calibration Optimization Method= 1
WQ AD Non Conservative
WQ ULTIMATE=-1
WQ Max Comp Step=1HOUR
WQ Output Interval=15MIN
WQ Output Selected Increments= 0
WQ Output face flow=0
WQ Output face velocity=0
WQ Output face area=0
WQ Output face dispersion=0
WQ Output cell volume=0
WQ Output cell surface area=0
WQ Output cell continuity=0
WQ Output cumulative cell continuity=0
WQ Output face conc=0
WQ Output face dconc_dx=0
WQ Output face courant=0
WQ Output face peclet=0
WQ Output face adv mass=0
WQ Output face disp mass=0
WQ Output cell mass=0
WQ Output cell source sink temp=0
WQ Output nsm pathways=0
WQ Output nsm derived pathways=0
WQ Create Restart=0
WQ Fixed Restart=0
WQ System Summary=0
WQ Write To DSS=0
Sorting and Armoring Iterations= 10
XS Update Threshold= 0.02
Bed Roughness Predictor= 0
Hydraulics Update Threshold= 0.02
Energy Slope Method= 1
Volume Change Method= 1
Sediment Retention Method= 0
Sediment TS Multiplier= 1
Warm Up Method= 0
XS Weighting Method= 0
Number of US Weighted Cross Sections= 1
Number of DS Weighted Cross Sections= 1
Upstream XS Weight=0
Main XS Weight=1
Downstream XS Weight=0
Number of DS XS's Weighted with US Boundary= 1
Upstream Boundary Weight= 1
Weight of XSs Associated with US Boundary= 0
Number of US XS's Weighted with DS Boundary= 1
Downstream Boundary Weight= 0.5
Weight of XSs Associated with DS Boundary= 0.5
Percentile Method= 0
Sediment Output Level= 3
Mass or Volume Output= 0
Output Increment Type= 1
Profile and TS Output Increment= 1
Transport Output Increment 1
XS Output Flag= 0
XS Output Increment= 10
Read HDF5 Sediment Hotstart= 0
Sediment Hotstart Type= 0
Write Gradation File= 0
Read Gradation Hotstart= 0
Write HDF5 File= 1
Write Binary Output= 1
Write DSS Sediment File= 0
DSS Sediment Output Type= 1
SV Curve= 0
Specific Gage Flag= 0
Subcell Erosion Methods= 0
Subcell Deposition Methods= 0
Advection Scheme= 1
Matrix Solver= 0
Implicit Weighting Factor= 1
Maximum Outer Loop Convergence Iterations= 5
Convergence Maximum Absolute= 0.001
Convergence RMSE= 0.0001
Grain Fractions Max Abs Error= 0.001
Max Subgrid Regions= 1
Max Subgrid Length Scale= 3.402823E+38
Initial Layer Thickness= 3.402823E+38
Min Layer Thickness= 3.402823E+38
Max Layer Thickness= 3.402823E+38
Number of Layers= 5

--- CLE-50-2.p01 (plan) ---

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Plan Title=Existing Conditions
Short Identifier=Existing
Geom File=g01
Flow File=f01
Existing 2023 conditions without improvements

--- CLE-50-2.p02 (plan) ---

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Plan Title=Partial Rock and Two Channel Alt
Short Identifier=Part Rock Alt
Geom File=g02
Flow File=f01
*Not Used
Alternative with rock channel lining and excavation to 513.4 ft at bridge from XS 1250 to 250. Channel widening with two-step channel from XS 1150 to 800.

--- CLE-50-2.p03 (plan) ---

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Plan Title=Partial Conc and Two Channel Alt
Short Identifier=Part Conc Alt
Geom File=g03
Flow File=f01
*Not Used
Alternative with concrete slope lining and excavation to 513.4 ft at bridge from XS 1250 to 250. Channel widening with two-step channel from XS 1150 to 800.

--- CLE-50-2.p04 (plan) ---

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Plan Title=Full Rock and Two Channel Alt
Short Identifier=Full Rock Alt
Geom File=g04
Flow File=f01
*Not Used
Alternative with rock channel lining and excavation to 513.4 ft at bridge from XS 1250 to 250. Channel widening with two-step channel from XS 1250 to 250.

--- CLE-50-2.p05 (plan) ---

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Plan Title=Full Rock and Two Channel Add Depth Alt
Short Identifier=Full Rockl Depth Alt
Geom File=g05
Flow File=f01
Std Step Tol= 0.001
Critical Tol= 0.001
Num of Std Step Trials= 40
*Not Used
Alternative with rock channel lining and excavation to 511.1 ft at bridge from XS 1250 to 100. Channel widening with two-step channel from XS 1250 to 100.

--- CLE-50-2.p06 (plan) ---

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Plan Title=Full Rock Excavation Add Depth Alt
Short Identifier=Full Rock Exc Depth Alt
Geom File=g06
Flow File=f01
Std Step Tol= 0.001
Critical Tol= 0.001
Num of Std Step Trials= 40
*Not Used
Alternative with rock channel lining and excavation to 511.1 ft at bridge from XS 1250 to 100. Channel widening l from XS 1250 to 100.

--- CLE-50-2.p07 (plan) ---

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Plan Title=Full Rock and Excavation Alt
Short Identifier=Alternative 1 and 3
Geom File=g07
Flow File=f01
Std Step Tol= 0.001
Critical Tol= 0.001
Num of Std Step Trials= 40
Alternative with rock channel lining and excavation to 513.4 ft at bridge from XS 1250 to 250. Channel widening from XS 1250 to 250.
DSS File=dss

--- CLE-50-2.p08 (plan) ---

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Plan Title=Full Conc and Excavation Alt
Short Identifier=Alternative 2
Geom File=g08
Flow File=f01
Std Step Tol= 0.001
Critical Tol= 0.001
Num of Std Step Trials= 40
Alternative with concrete slope lining and excavation to 513.4 ft at bridge from XS 1250 to 250. Channel widening from XS 1250 to 250.
DSS File=dss

--- CLE-50-2.p09 (plan) ---

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Plan Title=Full Conc and Two Channel Alt
Short Identifier=Full Conc Alt
Geom File=g09
Flow File=f01
*Not Used
Alternative with concrete slope lining and excavation to 513.4 ft at bridge from XS 1250 to 250. Channel widening with two-step channel from XS 1250 to 250.

--- CLE-50-2.p10 (plan) ---

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Plan Title=Full Conc and Two Channel Add Depth Alt
Short Identifier=Full Concl Depth Alt
Geom File=g10
Flow File=f01
Std Step Tol= 0.001
Critical Tol= 0.001
Num of Std Step Trials= 40
*Not Used
Alternative with concrete slope lining and excavation to 511.1 ft at bridge from XS 1250 to 100. Channel widening with two-step channel from XS 1250 to 100.

--- CLE-50-2.p11 (plan) ---

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Plan Title=Full Conc Excavation Add Depth Alt
Short Identifier=Full Conc Exc Depth Alt
Geom File=g11
Flow File=f01
Std Step Tol= 0.001
Critical Tol= 0.001
Num of Std Step Trials= 40
*Not Used
Alternative with concrete slope lining and excavation to 511.1 ft at bridge from XS 1250 to 100. Channel widening from XS 1250 to 100.

--- CLE-50-2.f01 (steady flow) ---

Flow Title=Existing Conditions
Program Version=6.10
BEGIN FILE DESCRIPTION:
Flood discharges from the USGS Stream Stats online tool.
END FILE DESCRIPTION:
Number of Profiles= 6
Profile Names=50% AEP,20% AEP,10% AEP,4% AEP,2% AEP,1% AEP
River Rch & RM=CLX_1,Reach           ,1750.000
     224     411     564     787     973    1180
Boundary for River Rch & Prof#=CLX_1,Reach           , 1
Up Type= 3
Up Slope=0.0187
Dn Type= 3
Dn Slope=0.0058
Boundary for River Rch & Prof#=CLX_1,Reach           , 2
Up Type= 3
Up Slope=0.0187
Dn Type= 3
Dn Slope=0.0058
DSS Import GetInterval= 0
DSS Import GetPeak= 0
DSS Import FillOption= 0

--- CLE-50-2.g19 (geometry) ---

Geom Title=Alternative 1 with Bench Sed Trap Energy
Program Version=6.10
BEGIN GEOM DESCRIPTION:
ODOT Mannings n:
Bare earth- 0.02
Rock Channel Protection- 0.4
Concrete- 0.015
HEC-RAS Manual Mannings n:
Natural Streams, 1. Minor Streams, b. Mountain streams, 1. Bottom: Gravels, cobbles and few
boulders- 0.040
Natural Streams, 2. Flood Plains, d. Trees, 1. Dense Willows, summer, straight- 0.120
Natural Streams, 2. Flood Plains, a. Pasture no brush, 1. short grass- 0.03
Natural Streams, 2. Flood Plains, c. Brush, 1. Scattered brush, heavy weeds- 0.05
Natural Streams, 2. Flood Plains, c. Brush, 3. Light brush and trees, in summer- 0.06
END GEOM DESCRIPTION:

River Reach=CLX_1           ,Reach
Reach XY= 29
    1469257.0675    430421.023251469188.67920462430333.623939497
1469161.96921142430290.2202005441469124.13005438430257.945625425
1469081.87982007430251.2308615051469047.46072519430240.640370774
1468966.09592794430201.1868898711468923.80510537430197.848140721
1468860.36205562430218.5768484191468793.59388851430220.106468389
 1468664.4379771430195.6307851691468582.13977566430174.476896669
1468563.22019714430161.1219000681468528.71978926430139.976488783
1468433.21226281 430103.846532171468322.83025833430094.346917063
1468264.64695202 430120.614809161468243.81319511430157.783150918
 1468230.4581985430181.1543949691468164.79613188430206.751471788
1468132.26581788430234.4625845151468079.10157036430256.832709041
1468039.59902399 430245.935616141467986.64657034430207.986357688
1467933.30952413430171.1381475191467874.86680489430225.583028552
1467814.22747111430253.4939598911467758.95101963430245.053075245
    1467739.9775    430243.32355

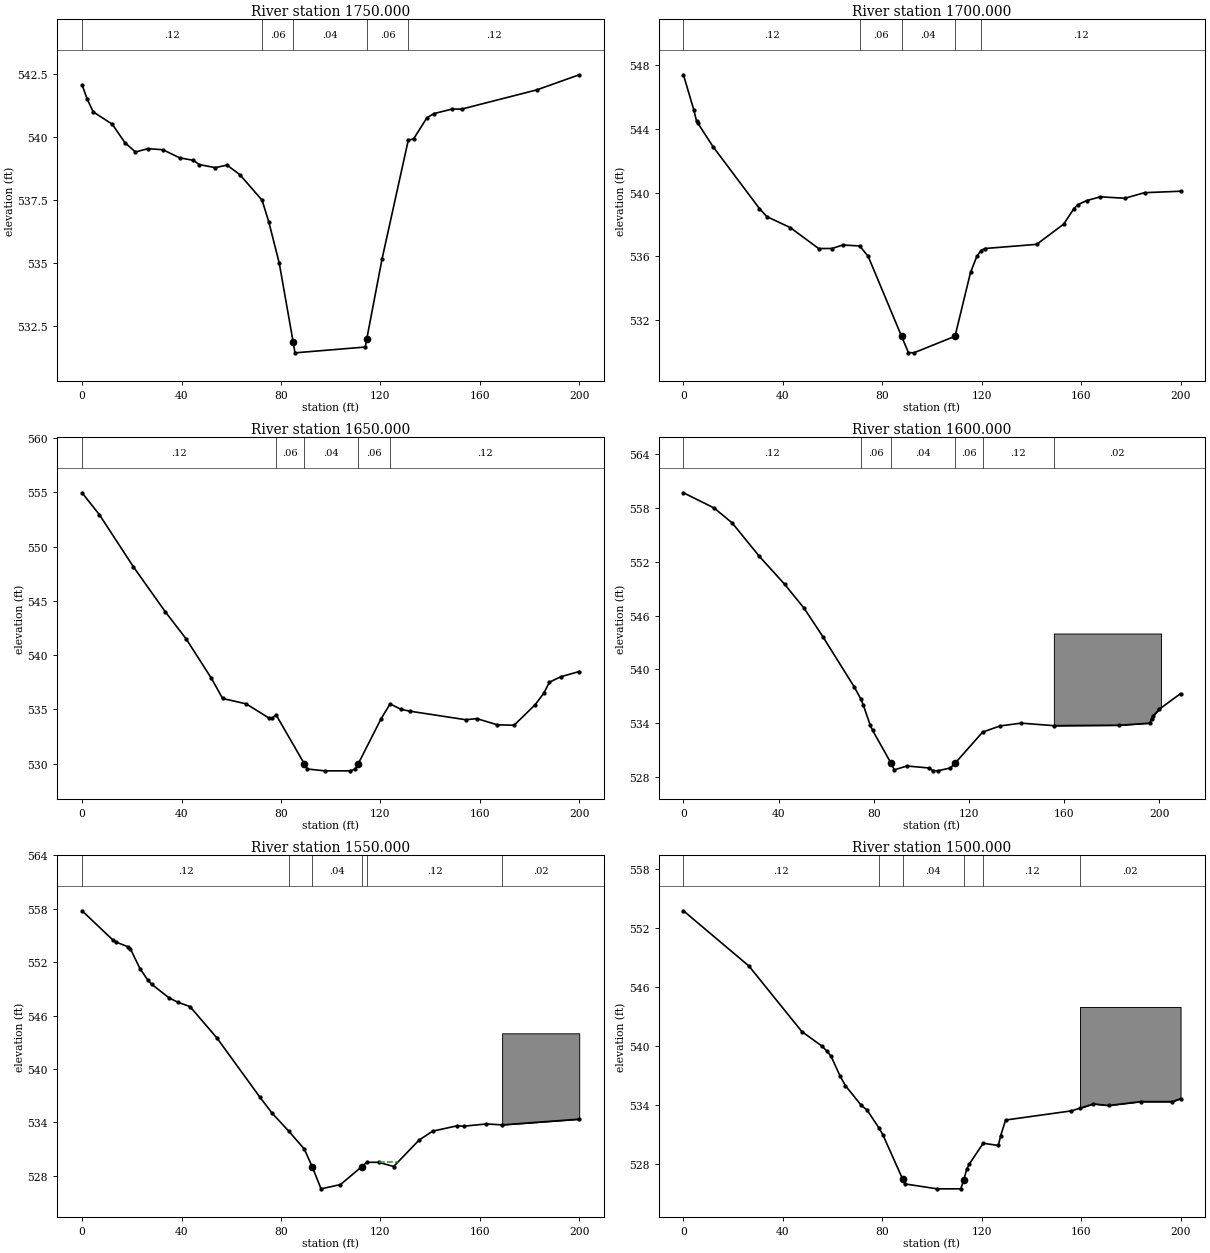
Type RM Length L Ch R = 1 ,1750.000,49.9,49.9,49.5
XS GIS Cut Line= 2
1469326.38890064 430347.778734431469171.27444681  430474.0304917
#Sta/Elev= 30
       0  542.07    2.08   541.5    4.48     541   12.15  540.51   17.23  539.78
   21.47  539.41   26.41  539.54   32.53   539.5   39.22  539.18   44.71  539.08
    47.2  538.91   53.59  538.79   58.32  538.89   63.49  538.51   72.42   537.5
   75.17  536.62   79.33     535   84.93  531.87   85.65  531.45  113.92  531.68
  114.53     532   120.7  535.18  131.23  539.88  133.37  539.93  138.69  540.76
  141.46  540.93  148.84  541.11  152.71  541.11  182.89  541.87     200  542.47
#Mann= 5 ,-1,0
       0     .12       0   72.42     .06       0   84.93     .04       0
  114.53     .06       0  131.23     .12       0
Bank Sta=84.93,114.53
XS Rating Curve= 0 ,0
Exp/Cntr=0.3,0.1

Type RM Length L Ch R = 1 ,1700.000,49.6,49.9,50.2
XS GIS Cut Line= 2
1469295.21815252 430312.148621631469136.83859914 430434.27935925
#Sta/Elev= 30
       0  547.39    4.14  545.21    5.26   544.5    5.71  544.38   11.88  542.89
    30.6     539   33.56   538.5      43  537.81   54.38   536.5   59.74   536.5
   64.11  536.72   70.93  536.66   74.35     536   87.75     531    90.5  529.98
   92.68  529.96  109.27     531   115.5     535  118.02     536  119.71  536.37
   121.3   536.5   142.1  536.76  152.99  538.03  157.09     539  158.64  539.24
  162.16   539.5  167.73  539.74  177.58  539.65  185.53     540     200  540.09
#Mann= 5 ,-1,0
       0     .12       0   70.93     .06       0   87.75     .04       0
  109.27     .06       0  119.71     .12       0
Bank Sta=87.75,109.27
XS Rating Curve= 0 ,0
Exp/Cntr=0.3,0.1

Type RM Length L Ch R = 1 ,1650.000,53,49.9,46.6
XS GIS Cut Line= 2
1469272.58155052 430280.216617131469101.91704675 430384.49330271
#Sta/Elev= 30
       0  554.95    6.97  552.93   20.64  548.13   33.43     544   41.83   541.5
   52.01  537.86   56.53     536   66.02   535.5   75.38  534.17   76.38  534.16
   78.01   534.5   89.36     530    90.6   529.5   97.56  529.33  107.81  529.33
  109.99   529.5  111.14     530  120.28  534.12  123.91   535.5  128.25     535
  131.76  534.83  154.33  534.04  158.82  534.14  167.08  533.57  173.79  533.53
  182.26  535.42  185.69  536.46  188.03   537.5  192.56     538     200  538.48
#Mann= 5 ,-1,0
       0     .12       0   78.01     .06       0   89.36     .04       0
  111.14     .06       0  123.91     .12       0
Bank Sta=89.36,111.14
XS Rating Curve= 0 ,0
Exp/Cntr=0.3,0.1

Type RM Length L Ch R = 1 ,1600.000,49.7,48.3,47.9
XS GIS Cut Line= 3
1469228.49092989 430218.579334531469090.59600032 430363.44129779
1469084.45968016430369.887650734
#Sta/Elev= 30
       0   559.7   12.91     558   20.47  556.34   31.93   552.6   42.51   549.5
   50.77   546.8   58.56  543.66   71.87     538   74.56  536.69   75.61     536
   78.52  533.76   79.51  533.19    87.3   529.5   88.62  528.79   93.94  529.22
  103.09     529  104.78  528.71  106.82  528.68  112.15     529  114.06   529.5
  125.72     533  133.06  533.69  141.91     534  155.66  533.72   183.2  533.77
  195.93     534   196.7   534.5  197.49  534.84     200  535.56   208.9   537.3
#Mann= 6 ,-1,0
       0     .12       0   74.56     .06       0    87.3     .04       0
  114.06     .06       0  125.72     .12       0  155.66     .02       0
#Block Obstruct= 1 ,-1
  155.66  200.66     544
Bank Sta=87.3,114.06
XS Rating Curve= 0 ,0
Exp/Cntr=0.3,0.1

Type RM Length L Ch R = 1 ,1550.000,49.1,45.1,45.1
XS GIS Cut Line= 2
1469174.82337258  430171.37860651469073.03934419 430343.54135382
#Sta/Elev= 30
       0  557.77   12.32   554.5    13.8  554.24   18.52  553.72   19.44   553.5
   23.27  551.28   26.39     550   28.06   549.5    34.9     548   38.44   547.5
   43.42     547   54.18   543.5   71.62  536.79   76.52     535   83.16     533
   89.37     531   92.59     529   96.14  526.52  103.96     527  112.46     529
  114.56   529.5  119.36   529.5  125.35  529.03  135.57     532  141.03     533
  150.81   533.6  153.55  533.56  162.56  533.81  168.99  533.71     200  534.35
#Mann= 6 ,-1,0
       0     .12       0   83.16     .06       0   92.59     .04       0
  112.46     .06       0  114.56     .12       0  168.99     .02       0
#XS Ineff= 1 ,-1
  119.36  126.93   529.5
Permanent Ineff=
       F
#Block Obstruct= 1 ,-1
  168.99     200     544
Bank Sta=92.59,112.46
XS Rating Curve= 0 ,0
Exp/Cntr=0.3,0.1

Type RM Length L Ch R = 1 ,1500.000,48.1,49.9,51.4
XS GIS Cut Line= 2
1469102.98790102 430151.646367221469051.28937508 430344.84901321
#Sta/Elev= 30
       0  553.79   26.35  548.17   47.64   541.5   55.84     540   57.76   539.5
   59.38     539   62.97     537   65.16     536   71.54     534   73.92   533.5
   78.72  531.67   80.23     531   88.26  526.46   89.11     526  102.05   525.5
  111.57   525.5  112.81  526.43  113.98   527.5  114.96     528   120.6  530.14
  126.69  529.91  127.61  530.89  129.61   532.5  156.02  533.43  159.53   533.7
  164.93  534.14  171.02  533.98  183.92  534.37  196.75  534.37     200  534.68
#Mann= 6 ,-1,0
       0     .12       0   78.72     .06       0   88.26     .04       0
  112.81     .06       0   120.6     .12       0  159.53     .02       0
#Block Obstruct= 1 ,-1
  159.53     200     544
Bank Sta=88.26,112.81
XS Rating Curve= 0 ,0
Exp/Cntr=0.3,0.1

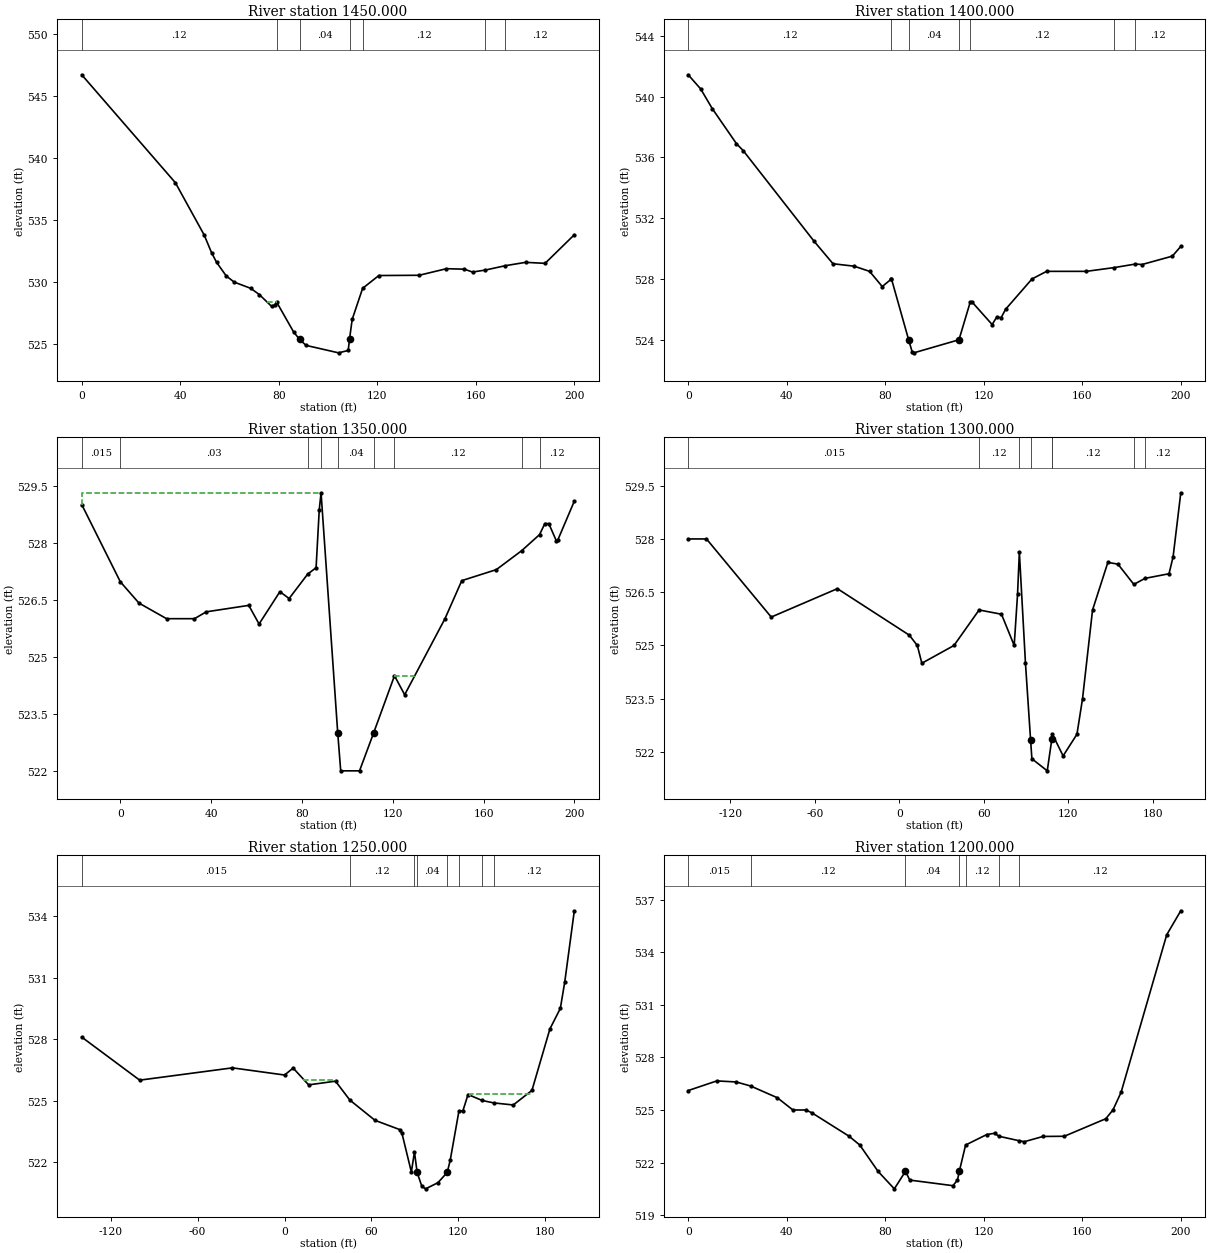
Type RM Length L Ch R = 1 ,1450.000,50,50,50
XS GIS Cut Line= 2
1469069.66951067 430142.11859626 1468989.1217821 430325.18160023
#Sta/Elev= 30
       0  546.68   38.01     538   49.72  533.79   52.73  532.36   54.73   531.6
   58.65   530.5   61.91     530   68.61   529.5   72.09     529   77.08  528.05
   78.43  528.18   79.08  528.41      86     526   88.46  525.39   91.06  524.91
  104.28  524.31  108.19   524.5  108.73  525.42  109.81     527  114.05   529.5
  120.64  530.53  136.99  530.55  148.08  531.08  155.34  531.04  158.66  530.81
  163.87  530.97  171.98  531.32  180.21  531.59  188.13  531.51     200  533.81
#Mann= 7 ,-1,0
       0     .12       0   79.08     .06       0   88.46     .04       0
  108.73     .06       0  114.05     .12       0  163.87     .02       0
  171.98     .12       0
#XS Ineff= 1 ,-1
   75.31   79.08  528.41
Permanent Ineff=
       F
Bank Sta=88.46,108.73
XS Rating Curve= 0 ,0
Exp/Cntr=0.3,0.1

Type RM Length L Ch R = 1 ,1400.000,52.8,48.3,45.5
XS GIS Cut Line= 2
1469020.68011032 430115.495880441468951.53032151 430303.16129203
#Sta/Elev= 30
       0  541.43    5.06   540.5    9.79   539.2   19.59   536.9   22.34  536.44
   51.16  530.47    58.8     529   67.37  528.84   73.64   528.5   78.79   527.5
   82.38  527.98   82.54     528    89.5     524   90.92  523.21   91.62  523.14
  109.94     524  114.55   526.5  115.16   526.5  123.41     525  125.34  525.51
  127.06  525.45  128.84     526  139.59     528  145.52   528.5  161.66   528.5
  173.07  528.75  181.57  528.98  184.27  528.95  196.57   529.5     200  530.14
#Mann= 7 ,-1,0
       0     .12       0   82.38     .06       0    89.5     .04       0
  109.94     .06       0  114.55     .12       0  173.07     .02       0
  181.57     .12       0
#XS Ineff= 1 ,-1
  115.16  131.79   526.5
Permanent Ineff=
       F
Bank Sta=89.5,109.94
XS Rating Curve= 0 ,0
Exp/Cntr=0.3,0.1

Type RM Length L Ch R = 1 ,1350.000,52.2,48.9,47.5
XS GIS Cut Line= 3
1468932.35740352430077.9568981711468933.28886647 430094.93136066
1468944.24725409 430294.63091935
#Sta/Elev= 30
     -17     529       0  526.97    8.22  526.41   20.37     526   32.67     526
   37.84  526.18   56.58  526.35   61.12  525.86    70.3  526.71   74.36  526.53
   82.51  527.17   86.24  527.34   87.63  528.86   88.43  529.31   95.77     523
   97.09     522  105.38     522  111.61     523  120.78   524.5  125.26     524
  143.02     526  150.42     527  165.66  527.29  176.86  527.79  184.68  528.21
  187.02   528.5  188.76   528.5  192.12  528.04  192.74  528.07     200  529.09
#Mann= 9 ,-1,0
     -17    .015       0       0     .03       0   82.51     .12       0
   88.43     .06       0   95.77     .04       0  111.61     .06       0
  120.78     .12       0  176.86     .02       0  184.68     .12       0
#XS Ineff= 2 ,-1
     -17   88.43  529.31  120.78  129.45   524.5
Permanent Ineff=
       F       F
Bank Sta=95.77,111.61
XS Rating Curve= 0 ,0
Exp/Cntr=0.3,0.1

Type RM Length L Ch R = 1 ,1300.000,49.1,50.6,52.6
XS GIS Cut Line= 5
1468800.51159995429971.7108152781468818.43772998430018.386867622
   1468836.36386430065.0629199661468854.28999002 430111.73897231
1468925.99451011 430298.44318169
#Sta/Elev= 30
    -150     528    -137     528     -91   525.8     -44   526.6    7.13  525.29
   12.79     525   16.02   524.5   38.85     525   56.69     526    72.6  525.88
   81.63     525   84.01  526.44    85.3  527.63   89.64   524.5   93.26  522.35
   94.21  521.81  105.12  521.47  108.36  522.36  108.82   522.5  116.38  521.89
  126.22   522.5  130.18   523.5  137.31     526  148.19  527.34  155.37  527.29
  166.64  526.72   174.6  526.89  191.64  527.02  194.55   527.5     200   529.3
#Mann= 8 ,-1,0
    -150    .015       0   56.69     .12       0    85.3     .06       0
   93.26     .04       0  108.36     .06       0  108.82     .12       0
  166.64     .02       0   174.6     .12       0
#XS Ineff= 2 ,-1
    -150    85.3  527.63  108.82  126.22   522.5
Permanent Ineff=
       F       F
Bank Sta=93.26,108.36
XS Rating Curve= 0 ,0
Exp/Cntr=0.3,0.1

Type RM Length L Ch R = 1 ,1250.000,47.9,49.5,51.6
XS GIS Cut Line= 4
1468800.17590239429983.0629387161468807.20846646430022.439874131
1468824.78987661 430120.882212671468859.95269692 430317.76688975
#Sta/Elev= 30
    -140   528.1    -100     526     -36   526.6       0  526.25    5.93  526.59
    16.6  525.77   35.17  525.95   45.04  525.03   62.43  524.04   79.48  523.59
   81.06   523.4   87.52  521.52   89.66   522.5    91.5   521.5   94.76  520.82
   97.35   520.7  105.87     521  112.27   521.5  114.33  522.09  120.37   524.5
  123.08   524.5  126.64   525.3  136.37  525.01  144.41  524.89  157.86  524.79
  170.75   525.5  183.16   528.5  190.35   529.5  193.38  530.78     200  534.26
#Mann= 8 ,-1,0
    -140    .015       0   45.04     .12       0   89.66     .06       0
    91.5     .04       0  112.27     .06       0  120.37     .12       0
  136.37     .02       0  144.41     .12       0
#XS Ineff= 3 ,-1
    12.7   34.99     526   84.15   89.66   522.5  128.28  170.75  525.34
Permanent Ineff=
       F       F       F
Bank Sta=91.5,112.27
XS Rating Curve= 0 ,0
Exp/Cntr=0.3,0.1

Type RM Length L Ch R = 1 ,1200.000,50,49.1,50.7
XS GIS Cut Line= 2
1468793.21742771 430122.856109111468792.01050113  430322.8524674
#Sta/Elev= 30
       0  526.11   11.62  526.66   19.49   526.6   25.32  526.37   36.18   525.7
   42.52     525   47.74     525   50.21  524.84   65.35   523.5   69.67     523
   77.07   521.5   83.69   520.5   88.22   521.5   89.96     521   107.5  520.68
  109.32     521  110.08   521.5  112.63     523  121.24   523.6  124.38  523.67
   126.2   523.5  134.22  523.25  136.46  523.19  144.07  523.49   152.7   523.5
  169.53   524.5  172.45     525  175.74     526  194.29     535     200  536.37
#Mann= 7 ,-1,0
       0    .015       0   25.32     .12       0   88.22     .04       0
  110.08     .06       0  112.63     .12       0   126.2     .02       0
  134.22     .12       0
#XS Ineff= 2 ,-1
   77.07   88.22   521.5  124.38  160.11  523.67
Permanent Ineff=
       F       F
Bank Sta=88.22,110.08
XS Rating Curve= 0 ,0
Exp/Cntr=0.3,0.1

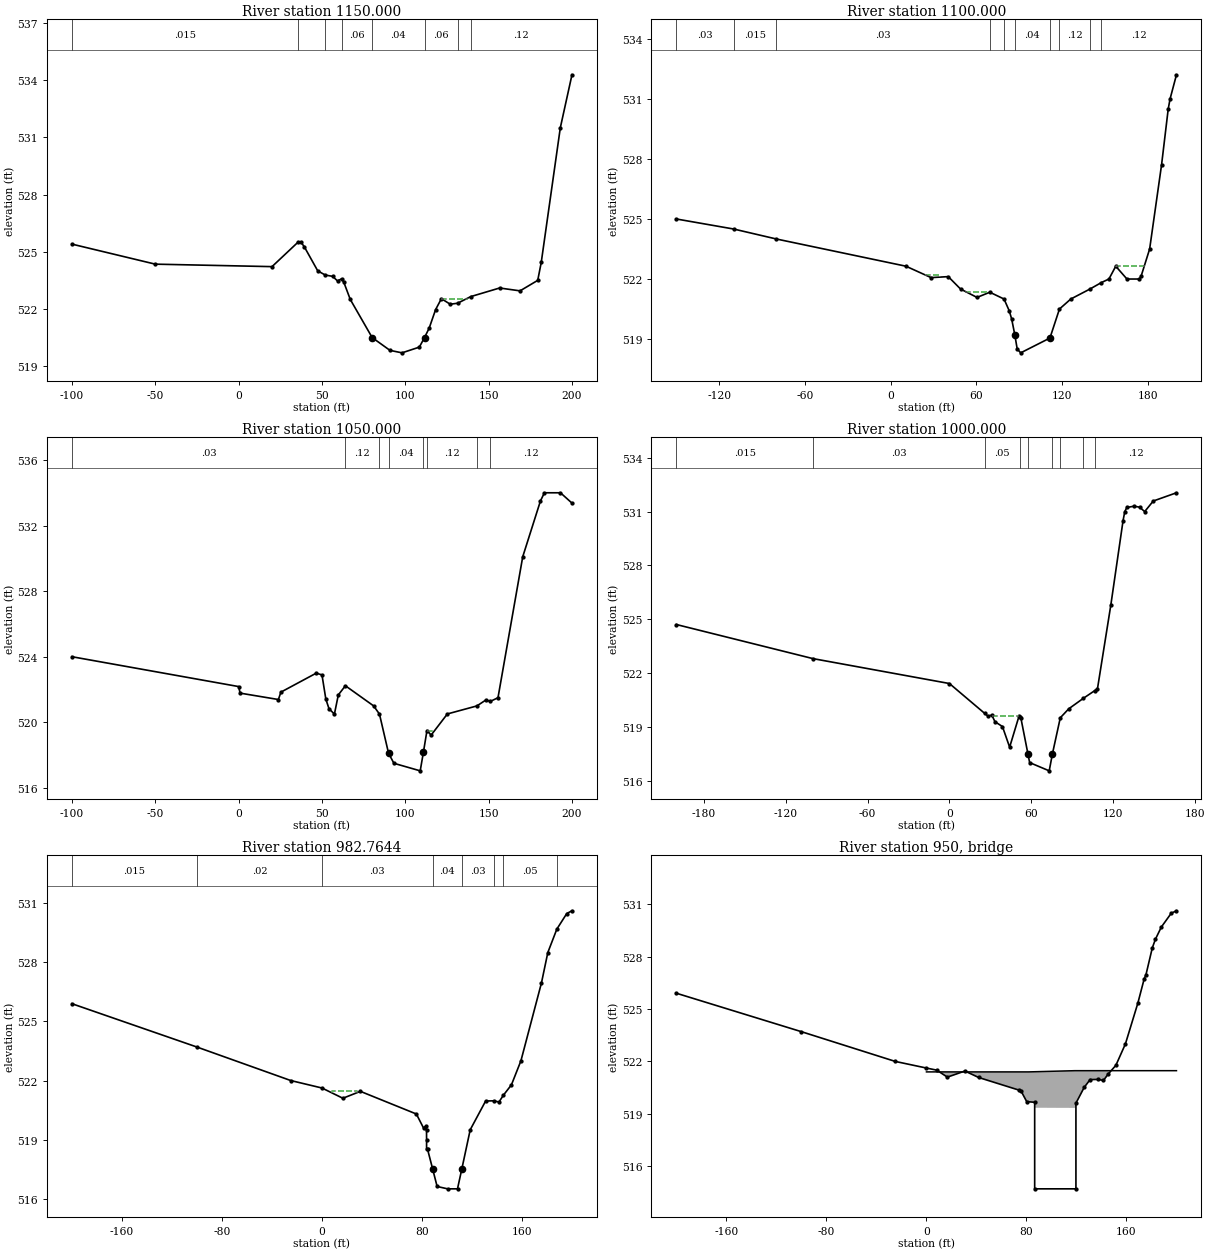
Type RM Length L Ch R = 1 ,1150.000,49.4,50,50
XS GIS Cut Line= 3
 1468770.3291533430013.2193880891468757.23592176 430112.35851905
1468731.04945867 430310.63678098
#Sta/Elev= 30
    -100   525.4     -50  524.35   20.02  524.22    35.6   525.5   37.42   525.5
    39.4  525.26   47.45     524   51.95  523.78   56.41  523.71   59.32  523.47
   61.77  523.58   63.11   523.4   66.98   522.5   80.12   520.5   90.79  519.83
   98.01   519.7  108.42     520  111.52   520.5  114.34     521  118.19  521.97
  121.66  522.54  126.93  522.25  131.34   522.3   139.3  522.65  156.59   523.1
  168.84  522.95  179.45   523.5  181.56  524.44     193   531.5     200  534.28
#Mann= 8 ,-1,0
    -100    .015       0    35.6     .03       0   51.95     .12       0
   61.77     .06       0   80.12     .04       0  111.52     .06       0
  131.34     .02       0   139.3     .12       0
#XS Ineff= 2 ,-1
                          121.69  137.66  522.54
Permanent Ineff=
       F       F
Bank Sta=80.12,111.52
XS Rating Curve= 0 ,0
Exp/Cntr=0.3,0.1

Type RM Length L Ch R = 1 ,1100.000,49.2,49.7,49.7
XS GIS Cut Line= 4
 1468737.2388876429954.5324565921468726.93071119430015.669527989
1468712.29975111  430102.44472611468679.04756912 430299.66108545
#Sta/Elev= 30
    -150     525    -110   524.5     -80     524   10.67  522.64   28.25  522.07
   40.25  522.12   48.86   521.5   60.39  521.08   69.34  521.34    79.3     521
   82.95  520.41   84.65     520   86.84  519.21   88.52   518.5   90.97  518.31
  111.42  519.05  118.09   520.5  126.02     521  139.45   521.5  147.36  521.82
  152.72     522  157.51  522.64  165.34     522  174.08     522  175.33  522.16
  181.22   523.5  189.59  527.72  194.23   530.5  195.51     531     200  532.21
#Mann= 10 ,-1,0
    -150     .03       0    -110    .015       0     -80     .03       0
   69.34     .12       0    79.3     .06       0   86.84     .04       0
  111.42     .06       0  118.09     .12       0  139.45     .02       0
  147.36     .12       0
#XS Ineff= 3 ,-1
   24.11    34.4  522.19   52.22   67.52  521.35  157.97   178.5  522.64
Permanent Ineff=
       F       F       F
Bank Sta=86.84,111.42
XS Rating Curve= 0 ,0
Exp/Cntr=0.3,0.1

Type RM Length L Ch R = 1 ,1050.000,48.2,49.7,51.3
XS GIS Cut Line= 3
1468702.53743758430004.1422907271468665.14676491 430093.15716821
1468628.07789209 430289.69189458
#Sta/Elev= 30
    -100     524       0  522.18     .87  521.78   23.85  521.39   25.35  521.84
   46.59     523      50  522.89   52.33  521.41   54.22  520.83   57.46   520.5
    59.8  521.67   64.05  522.23   81.01     521    84.5   520.5   89.93  518.12
   93.15   517.5  108.94  517.04   110.9   518.2     113   519.5   115.5  519.22
  125.23  520.51  142.96     521  148.48  521.37  150.91  521.27  155.61   521.5
  170.46   530.1  181.08   533.5  183.46     534  193.09     534     200  533.37
#Mann= 8 ,-1,0
    -100     .03       0   64.05     .12       0    84.5     .06       0
   89.93     .04       0   110.9     .06       0     113     .12       0
  142.96     .02       0  150.91     .12       0
#XS Ineff= 4 ,-1
     -50   46.59     523      50   64.05  522.23     113  117.15   519.5
  148.48  154.96  521.37
Permanent Ineff=
       F       F       F       F
Bank Sta=89.93,110.9
XS Rating Curve= 0 ,0
Exp/Cntr=0.3,0.1

Type RM Length L Ch R = 1 ,1000.000,7.4,15.9,10.3
XS GIS Cut Line= 3
1468731.62975802429948.2758093491468621.38432022430116.251121665
1468567.12800099 430272.39077914
#Sta/Elev= 30
    -200   524.7    -100   522.8       0  521.41   25.75  519.75   28.29  519.59
   31.05  519.65   33.37  519.28   38.85  519.01   44.11  517.86   51.06  519.61
   51.74  519.56   52.32   519.5   57.48   517.5   58.78     517   73.11  516.54
    75.5   517.5   81.23   519.5   87.42     520   98.22  520.59  106.59  521.02
  108.47  521.12  118.28   525.8  127.23   530.5  128.48     531  129.97  531.23
  135.12   531.3   139.3  531.25  143.06     531  149.35  531.59  166.35  532.05
#Mann= 9 ,-1,0
    -200    .015       0    -100     .03       0   25.75     .05       0
   51.74     .06       0   57.48     .04       0    75.5     .06       0
   81.23     .12       0   98.22     .02       0  106.59     .12       0
#XS Ineff= 2 ,-1
   27.34   30.24  519.61   31.52   51.06  519.61
Permanent Ineff=
       F       F
Bank Sta=57.48,75.5
XS Rating Curve= 0 ,0
Exp/Cntr=0.5,0.3

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
Type RM Length L Ch R = 1 ,982.7644,62.7,61,60.7
XS GIS Cut Line= 3
1468746.14501959429919.9584453481468637.05306538 430087.58584623
1468527.96111117 430255.21324711
#Sta/Elev= 30
    -200   525.9    -100   523.7     -25     522       0  521.62   16.72   521.1
   30.75  521.45   75.52   520.3   81.23  519.59   83.39   519.7   83.64   519.5
   83.68     519    83.7   518.5    84.5   518.5   88.57   517.5   92.12  516.62
   100.5   516.5  108.42   516.5  111.85   517.5  118.59   519.5  130.93  520.96
  137.46  520.97  141.61  520.91   145.2  521.26  151.56  521.78  159.15     523
   175.6  526.96  180.68   528.5   187.9  529.69  195.84  530.48     200  530.62
#Mann= 8 ,-1,0
    -200    .015       0    -100     .02       0       0     .03       0
   88.57     .04       0  111.85     .03       0  137.46     .02       0
   145.2     .05       0   187.9     .02       0
#XS Ineff= 1 ,-1
    8.24   28.34  521.47
Permanent Ineff=
       F
Bank Sta=88.57,111.85
XS Rating Curve= 0 ,0
Exp/Cntr=0.5,0.3

Type RM Length L Ch R = 3 ,950     ,,,
Bridge Culvert--1,0,-1,-1, 0
Deck Dist Width WeirC Skew NumUp NumDn MinLoCord MaxHiCord MaxSubmerge Is_Ogee
11.3,36,2.6,0, 4, 4, , , 0.98, 0, 0,0,,
       0   81.62   118.8     200
   521.4   521.4  521.47  521.47
  519.35  519.35  519.34  519.34
       0   86.75  123.93     200
   519.3   519.3  519.43  519.43
  517.21  517.21   517.3   517.3
BR Coef=-1 , 0 , 0 ,, 0 ,,,0.8,-1,1.2,0,
WSPro=,,,, 1 ,,,, 0 ,,,, 0 ,,,,-1 ,-1 ,-1 , 0 , 0 , 0 , 0 , 0
BR U #Sta/Elev= 30
    -200   525.9    -100   523.7     -25     522       0  521.62    8.24   521.5
   16.72   521.1   30.75  521.45   41.74  521.08    73.9  520.36   75.84  520.28
   80.19   519.7   86.57  519.66   86.57 514.708  119.57 514.708  119.57  519.61
  126.24  520.52  130.93  520.96  137.46  520.97  141.61  520.91   145.2  521.26
  151.56  521.78  159.15     523  169.09  525.33  174.16  526.72   175.6  526.96
  180.68   528.5  183.22     529   187.9  529.69  195.84  530.48     200  530.62
BR U #Mann= 8
    -200    .015    -100     .02       0     .03   86.57     .04  119.57     .03
  137.46     .02   145.2     .05   187.9     .02
BR U Banks=86.57,119.57
BR D #Sta/Elev= 30
    -120     524     -60     522     -30     522    17.6  521.54   32.87  521.88
    41.1  521.28   48.31  521.82   53.66   521.3   59.51   521.4   62.88  521.39
   69.13  520.92   76.09  520.73   79.44   520.5   83.11     520   83.11   513.4
  116.11   513.4  116.11  520.23  129.91  520.32  133.59  520.28  135.02  520.06
  135.61  520.11  135.92  520.46  141.61  520.82  149.99  520.62  153.43     520
  154.42  520.04   171.4  520.54     200  521.89     225  522.74     250  523.58
BR D #Mann= 6
    -120    .015   59.51     .03   83.11     .04  116.11     .03  154.42    .015
     225     .03
BR D Banks=83.11,116.11
BC Design=,, 0 ,, 0 ,,,,,,
BC Use User HTab Curves=0
BC User HTab FreeFlow(D)= 0

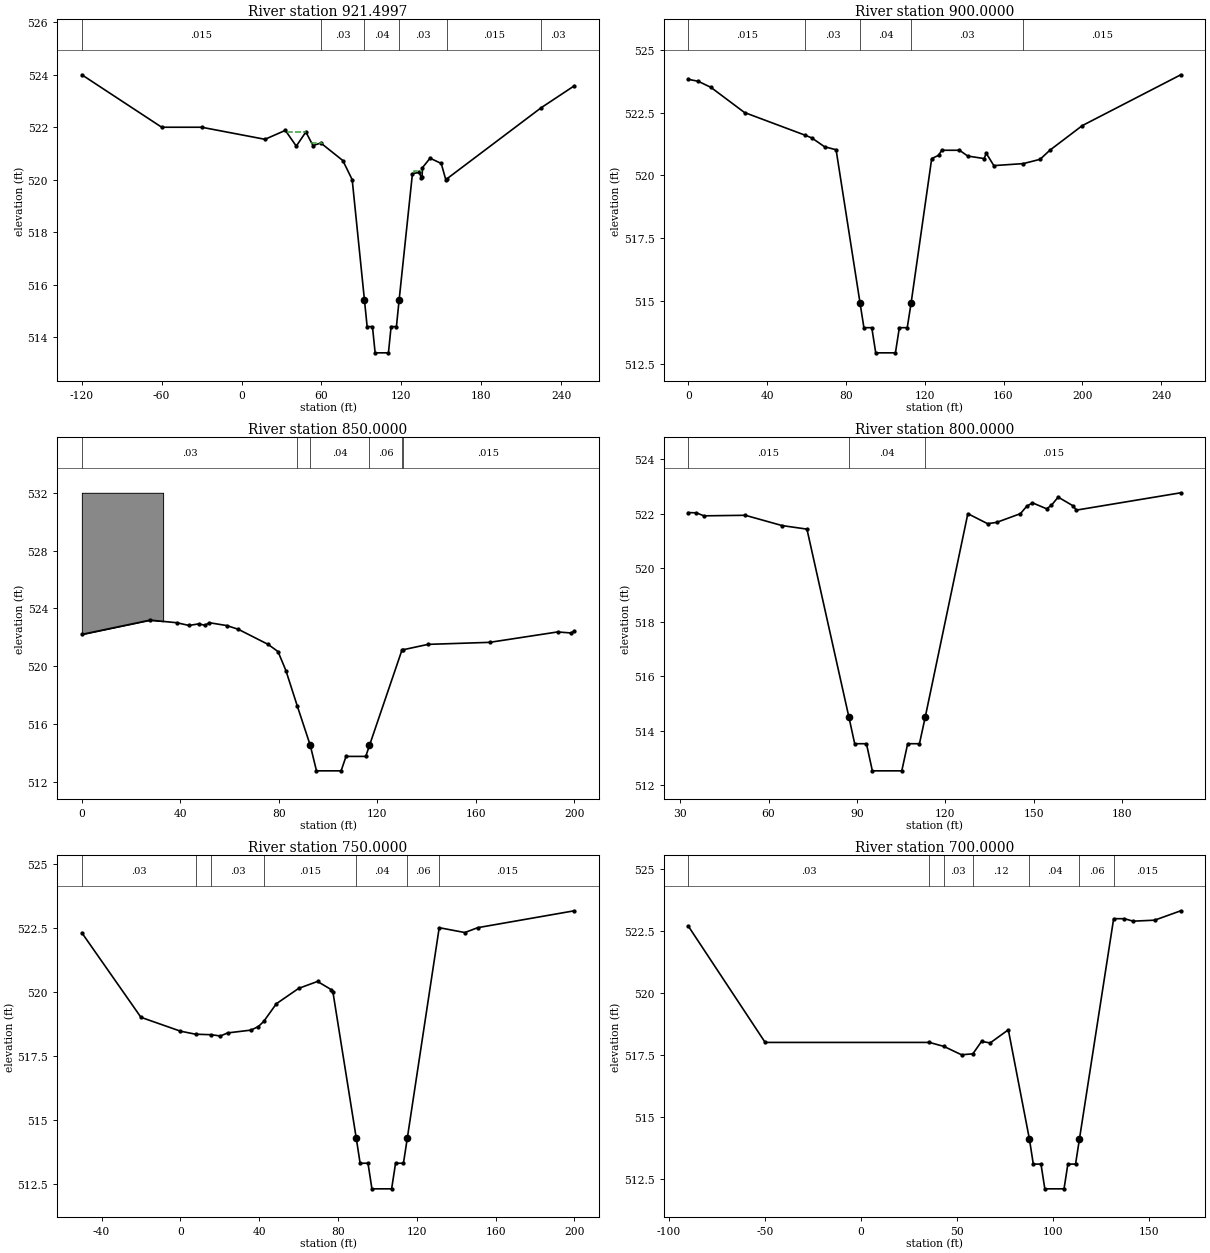
Type RM Length L Ch R = 1 ,921.4997,22.4,20.5,19.3
XS GIS Cut Line= 5
1468676.14883567429973.0940408371468661.25635643429986.443724806
1468585.70485838 430054.168420341468476.61290417 430221.79582122
1468449.33991562 430263.70267144
#Sta/Elev= 30
    -120     524     -60     522     -30     522    17.6  521.54   32.87  521.88
    41.1  521.28   48.31  521.82   53.66   521.3   59.51   521.4   76.09  520.73
   83.11     520   92.34   515.4   94.34   514.4   98.34   514.4  100.34   513.4
  110.34   513.4  112.34   514.4  116.34   514.4  118.34   515.4  128.37  520.23
  133.59  520.28  135.02  520.06  135.61  520.11  135.92  520.46  141.61  520.82
  149.99  520.62  153.43     520  154.42  520.04     225  522.74     250  523.58
#Mann= 6 ,-1,0
    -120    .015       0   59.51     .03       0   92.34     .04       0
  118.34     .03       0  154.42    .015       0     225     .03       0
#XS Ineff= 5 ,-1
     -30   32.87  521.88    33.9    48.2  521.82   52.48   60.36  521.41
  129.91  135.92  520.32  141.61  178.45  520.82
Permanent Ineff=
       F       F       F       F       F
Bank Sta=92.34,118.34
XS Rating Curve= 0 ,0
Exp/Cntr=0.5,0.3

Type RM Length L Ch R = 1 ,900.0000,49.8,49.8,49.8
XS GIS Cut Line= 3
1468547.13385365 430036.952217391468473.94643698430222.823006603
1468445.92329937430265.994281878
#Sta/Elev= 29
       0  523.82    5.07  523.74   11.47   523.5   28.52   522.5   59.24   521.6
    62.7  521.49   69.15  521.14   75.02  521.02  87.135 514.949  89.135 513.949
  93.135 513.949  95.135 512.949 105.135 512.949 107.135 513.949 111.135 513.949
 113.135 514.949  123.55  520.67  127.08   520.8  128.62     521  137.66     521
  141.84  520.77  150.17  520.67  151.24  520.88   155.1  520.39  170.07  520.47
  178.57  520.64  183.51     521     200  521.98     250     524
#Mann= 5 ,-1,0
       0    .015       0   59.24     .03       0  87.135     .04       0
 113.135     .03       0  170.07    .015       0
#XS Ineff= 1 ,-1
  137.66  183.51     521
Permanent Ineff=
       F
Bank Sta=87.135,113.135
XS Rating Curve= 0 ,0
Exp/Cntr=0.3,0.1

Type RM Length L Ch R = 1 ,850.0000,51.1,50.8,49.2
XS GIS Cut Line= 2
1468491.68972291 430018.089518641468435.89246107 430210.14853449
#Sta/Elev= 26
       0  522.19    27.7  523.18   38.51     523   43.52  522.81   47.48  522.92
   49.97  522.82   51.78     523   58.93   522.8   63.59  522.54   75.63   521.5
   79.67     521   82.86  519.69   87.55   517.2   92.77   514.5   95.29  512.74
  105.29  512.74  107.29  513.74  115.29  513.74  116.81   514.5  130.05  521.13
  130.28  521.12  140.62   521.5  165.62  521.64  193.18  522.36  198.69  522.29
     200  522.43
#Mann= 6 ,-1,0
       0     .03       0   87.55     .06       0   92.77     .04       0
  116.81     .06       0  130.05     .12       0  130.28    .015       0
#Block Obstruct= 1 ,-1
       0      33     532
Bank Sta=92.77,116.81
XS Rating Curve= 0 ,0
Exp/Cntr=0.3,0.1

Type RM Length L Ch R = 1 ,800.0000,50.5,49.9,48.5
XS GIS Cut Line= 2
1468426.90854645430036.5671496951468397.70031941  430201.2672788
#Sta/Elev= 26
   32.73  522.04   35.48  522.03   38.02  521.92   52.08  521.94    64.6  521.56
   73.02  521.43  87.235 514.517  89.235 513.517  93.235 513.517  95.235 512.517
 105.235 512.517 107.235 513.517 111.235 513.517 113.235 514.517  127.67     522
  134.38  521.63   137.5  521.68  145.53     522  147.65  522.27  149.62   522.4
  154.41  522.18  156.06  522.31  158.35  522.61  163.39  522.29   164.5  522.13
     200  522.77
#Mann= 3 ,-1,0
   32.73    .015       0  87.235     .04       0 113.235    .015       0
Bank Sta=87.235,113.235
XS Rating Curve= 0 ,0
Exp/Cntr=0.3,0.1

Type RM Length L Ch R = 1 ,750.0000,51,50.9,50.5
XS GIS Cut Line= 3
1468371.48612002 429947.609549891468369.48537408 429997.56950401
1468361.48239031 430197.40932049
#Sta/Elev= 27
     -50   522.3     -20     519       0  518.46    7.72  518.34   15.73  518.32
   20.36  518.27   23.97  518.39   35.85   518.5   39.62  518.64   42.33  518.84
   48.74  519.53   60.07  520.13   69.63   520.4   76.63  520.08   77.43     520
  89.255 514.302  91.255 513.302  95.255 513.302  97.255 512.302 107.255 512.302
 109.255 513.302 113.255 513.302 115.255 514.302  131.41   522.5  144.43  522.31
  150.94   522.5     200  523.16
#Mann= 7 ,-1,0
     -50     .03       0    7.72     .02       0   15.73     .03       0
   42.33    .015       0  89.255     .04       0 115.255     .06       0
  131.41    .015       0
Bank Sta=89.255,115.255
XS Rating Curve= 0 ,0
Exp/Cntr=0.3,0.1

Type RM Length L Ch R = 1 ,700.0000,62.2,56.4,51.2
XS GIS Cut Line= 3
1468347.67182205 429914.50974402 1468314.2359719 429997.53869117
1468316.40262427430163.201654615
#Sta/Elev= 22
     -90   522.7     -50     518   35.52     518   43.01  517.84   52.26   517.5
   58.15  517.54   62.65  518.04   67.18  517.98   76.61  518.51   87.61 514.083
   89.61 513.083   93.61 513.083   95.61 512.083  105.61 512.083  107.61 513.083
  111.61 513.083  113.61 514.083 131.444     523  137.07     523  141.58   522.9
  152.77  522.94   166.4  523.32
#Mann= 7 ,-1,0
     -90     .03       0   35.52     .02       0   43.01     .03       0
   58.15     .12       0   87.61     .04       0  113.61     .06       0
 131.444    .015       0
#XS Ineff= 1 ,-1
     -90   76.61  518.51
Permanent Ineff=
       F
Bank Sta=87.61,113.61
XS Rating Curve= 0 ,0
Exp/Cntr=0.3,0.1