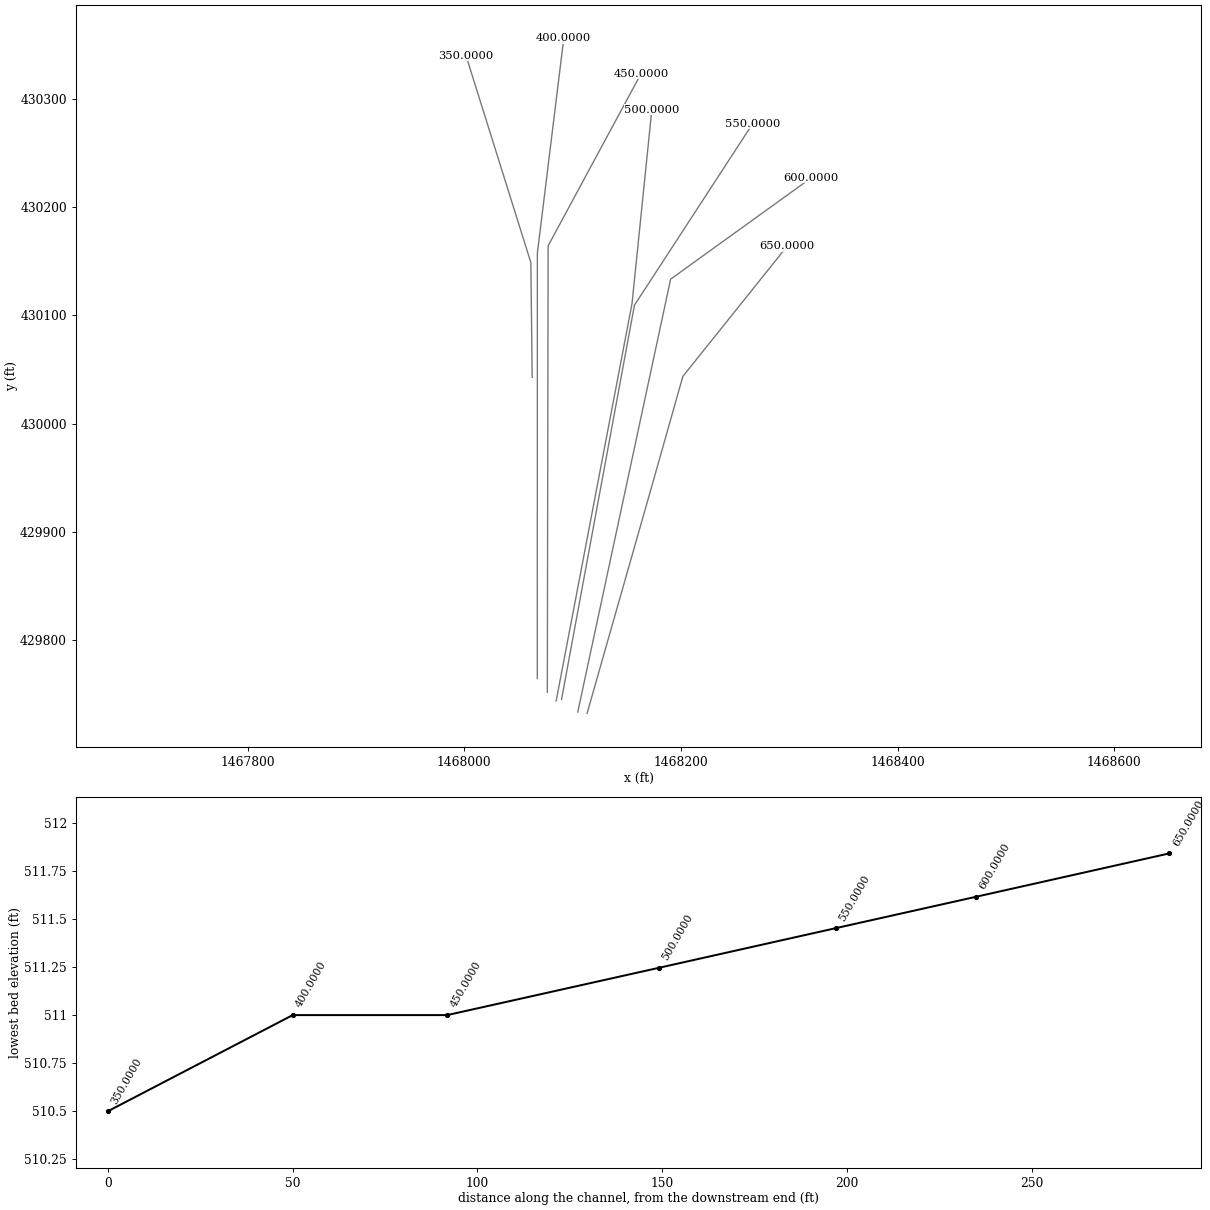
HEC-RAS study CLE-50-2.prj: CLE-50-2.25

--- CLE-50-2.g19 (geometry) --- (continued)

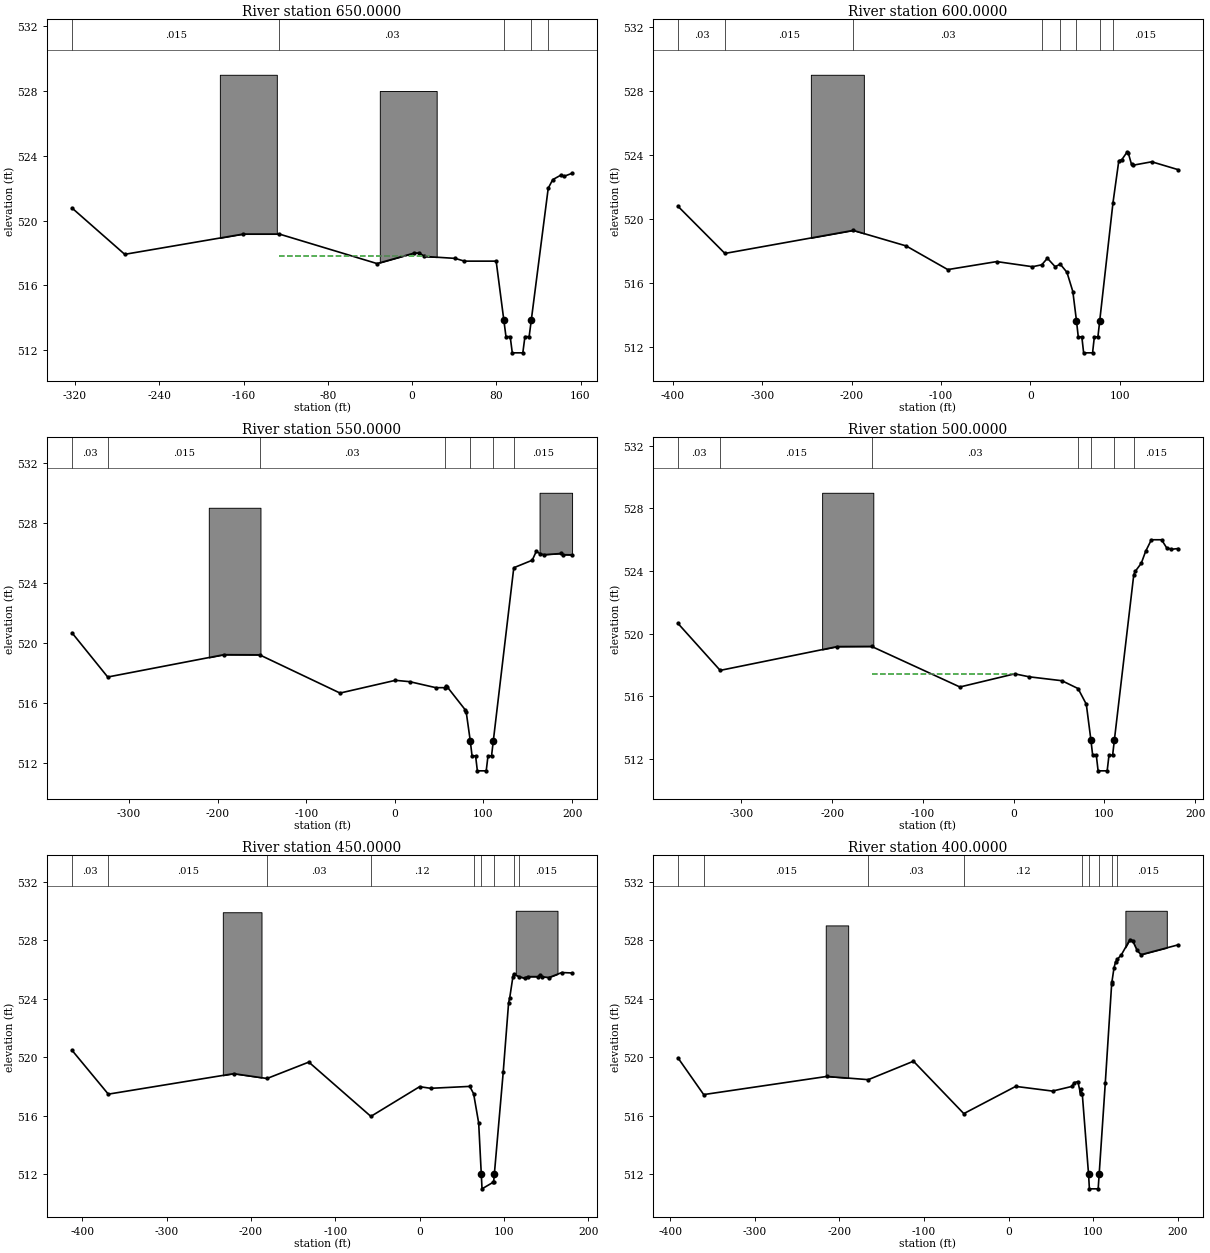
Type RM Length L Ch R = 1 ,650.0000,54.9,52.4,51.4
XS GIS Cut Line= 4
1468113.27637661429732.4024439161468172.87876954429941.595156356
1468201.69242222 430043.499807181468297.92692726 430163.64328688
#Sta/Elev= 24
 -322.93  520.78 -272.84  517.92 -160.49  519.17 -125.99  519.17  -33.26  517.35
    2.19     518    6.97     518   11.81  517.79   40.87  517.67   49.78   517.5
    79.9   517.5   87.22 513.841   89.22 512.841   93.22 512.841   95.22 511.841
  105.22 511.841  107.22 512.841  111.22 512.841  113.22 513.841  129.34     522
  133.64  522.53  141.74  522.82  144.16  522.73     152  522.92
#Mann= 5 ,-1,0
 -322.93    .015       0 -125.99     .03       0   87.22     .04       0
  113.22     .06       0  129.34    .015       0
#XS Ineff= 2 ,-1
 -322.93 -160.49  519.17 -125.99   15.73   517.8
Permanent Ineff=
       F       F
#Block Obstruct= 2 ,-1
  -182.5  -128.4     529   -30.6    23.4     528
Bank Sta=87.22,113.22
XS Rating Curve= 0 ,0
Exp/Cntr=0.3,0.1

Type RM Length L Ch R = 1 ,600.0000,35,37.9,40.1
XS GIS Cut Line= 3
1468104.69286019429733.6207019661468190.40888511430133.257753229
1468320.13174031430226.751702923
#Sta/Elev= 30
 -394.33  520.78 -341.77  517.83 -198.25  519.27    -139   518.3  -92.39  516.82
  -37.61  517.32    2.39     517   12.79  517.12   19.08  517.53   27.78     517
   33.48  517.16   40.96  516.65   47.55  515.45   51.63 513.615   53.63 512.615
   57.63 512.615   59.63 511.615   69.63 511.615   71.63 512.615   75.63 512.615
   77.63 513.615   92.48     521   98.98  523.62  102.46   523.7  108.26  524.17
  109.54  524.12  113.22   523.4  114.36  523.34  135.85  523.56  165.28  523.07
#Mann= 8 ,-1,0
 -394.33     .03       0 -341.77    .015       0 -198.25     .03       0
   12.79     .12       0   33.48     .06       0   51.63     .04       0
   77.63     .06       0   92.48    .015       0
#XS Ineff= 3 ,-1
 -394.33 -198.25  519.27    -139   19.08  517.53   24.46   33.48  517.16
Permanent Ineff=
       F       F       F
#Block Obstruct= 1 ,-1
  -245.6  -186.3     529
Bank Sta=51.63,77.63
XS Rating Curve= 0 ,0
Exp/Cntr=0.3,0.1

Type RM Length L Ch R = 1 ,550.0000,44,47.8,51.8
XS GIS Cut Line= 3
1468089.71680587429745.3686937781468157.00660937  430109.2092995
1468266.14806495 430276.80447447
#Sta/Elev= 29
 -364.26  520.66 -323.94  517.71 -192.89   519.2 -152.56  519.19  -61.83  516.64
     .66  517.49   16.78   517.4   46.27     517   56.45     517   57.47  517.09
   59.42  517.03   79.72   515.5   80.49   515.4  85.125 513.452  87.125 512.452
  91.125 512.452  93.125 511.452 103.125 511.452 105.125 512.452 109.125 512.452
 111.125 513.452  134.22     525  155.02   525.5  159.66   526.1  164.15  525.92
  168.39  525.87  187.56  525.95  189.89  525.87     200  525.86
#Mann= 7 ,-1,0
 -364.26     .03       0 -323.94    .015       0 -152.56     .03       0
   56.45     .12       0  85.125     .04       0 111.125     .06       0
  134.22    .015       0
#XS Ineff= 2 ,-1
 -364.26 -192.89   519.2 -152.56     .66  517.49
Permanent Ineff=
       F       F
#Block Obstruct= 2 ,-1
  -209.9  -151.6     529   163.3     200     530
Bank Sta=85.125,111.125
XS Rating Curve= 0 ,0
Exp/Cntr=0.3,0.1

Type RM Length L Ch R = 1 ,500.0000,60.7,57.3,53.5
XS GIS Cut Line= 3
1468084.73336115429743.8986369651468154.77759391 430110.72345484
1468173.05097918430289.673024693
#Sta/Elev= 27
    -370  520.66 -323.46  517.66 -194.44  519.18 -156.57  519.19  -59.26   516.6
    1.16  517.44   17.07  517.25   53.15     517   70.96   516.5   80.05   515.5
   85.06 513.246   87.06 512.246   91.06 512.246   93.06 511.246  103.06 511.246
  105.06 512.246  109.06 512.246  111.06 513.246  132.39  523.78  134.23     524
  140.63   524.5  145.43  525.26  151.76     526     163     526  168.47   525.5
  173.81  525.39  181.16  525.44
#Mann= 7 ,-1,0
    -370     .03       0 -323.46    .015       0 -156.57     .03       0
   70.96     .12       0   85.06     .04       0  111.06     .06       0
  132.39    .015       0
#XS Ineff= 3 ,-1
                            -370 -156.57  519.19 -156.57       0  517.44
Permanent Ineff=
       F       F       F
#Block Obstruct= 1 ,-1
  -211.1  -154.7     529
Bank Sta=85.06,111.06
XS Rating Curve= 0 ,0
Exp/Cntr=0.3,0.1

Type RM Length L Ch R = 1 ,450.0000,38.9,41.8,44.8
XS GIS Cut Line= 3
1468076.57499801429751.8331059291468077.32314336430164.061194277
1468163.15318918 430323.11235073
#Sta/Elev= 30
 -412.47  520.47 -369.37  517.47 -220.68  518.87 -181.03  518.54 -131.46  519.66
  -57.82  515.95       0  517.98    13.1  517.87    59.5     518   64.08   517.5
   70.09   515.5   73.19     512   74.06     511   87.58  511.46    87.9   511.5
   88.67     512   99.22  518.98  105.62  523.73  106.94  524.06  110.73   525.5
  111.57  525.66  118.13   525.5   124.5  525.39  128.03   525.5  140.85   525.5
  142.71  525.63  144.99  525.49   153.4  525.44  168.75  525.78  180.92  525.75
#Mann= 9 ,-1,0
 -412.47     .03       0 -369.37    .015       0 -181.03     .03       0
  -57.82     .12       0   64.08     .06       0   73.19     .04       0
   88.67     .06       0  111.57     .12       0  118.13    .015       0
#XS Ineff= 1 ,-1
 -412.47 -131.46  519.66
Permanent Ineff=
       F
#Block Obstruct= 2 ,-1
  -233.5  -187.6   529.9   114.1   163.6     530
Bank Sta=73.19,88.67
XS Rating Curve= 0 ,0
Exp/Cntr=0.3,0.1

Type RM Length L Ch R = 1 ,400.0000,46.2,50,52.5
XS GIS Cut Line= 3
1468067.33442339429764.5123954591468067.37900316 430157.09751214
1468091.76949029 430355.60470127
#Sta/Elev= 30
 -390.81  519.95 -360.39  517.44 -214.92  518.68 -165.95  518.46 -112.57  519.72
  -53.09  516.14    8.21     518    51.7  517.68   74.76     518   77.21  518.25
   81.67  518.33   84.78   517.5   85.03   517.8   86.83  517.51   94.28     512
   95.27     511  105.64     511  106.81     512  114.01   518.2  121.57     525
  121.89  525.14  124.34   526.1  126.17   526.5   128.4  526.69  133.12     527
  143.14  528.03  146.29  527.96  151.65  527.29  156.17     527     200  527.67
#Mann= 9 ,-1,0
 -390.81     .03       0 -360.39    .015       0 -165.95     .03       0
  -53.09     .12       0   86.83     .06       0   94.28     .04       0
  106.81     .06       0  121.89     .12       0   128.4    .015       0
#XS Ineff= 1 ,-1
 -112.57   81.67  518.33
Permanent Ineff=
       F
#Block Obstruct= 2 ,-1
  -216.2  -189.7     529   137.8   186.7     530
Bank Sta=94.28,106.81
XS Rating Curve= 0 ,0
Exp/Cntr=0.3,0.1

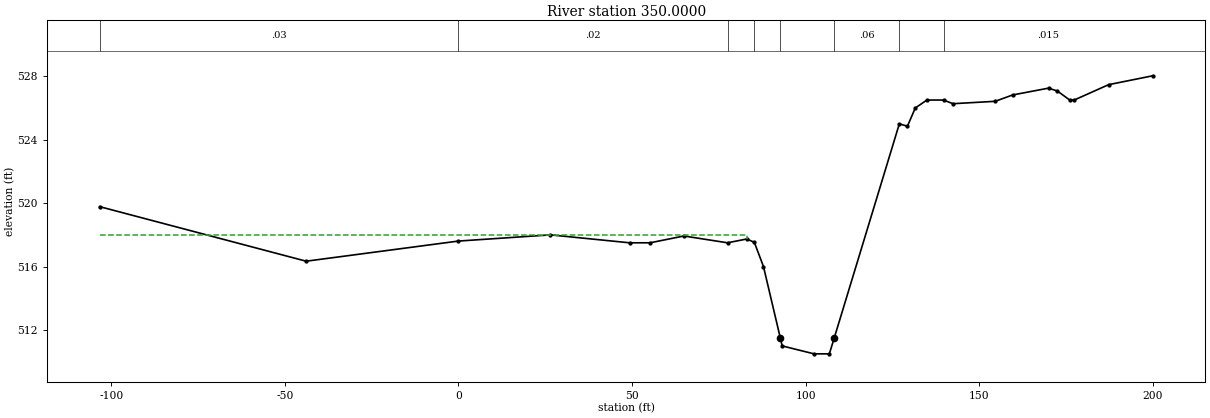
Type RM Length L Ch R = 1 ,350.0000,46.7,49.3,52.2
XS GIS Cut Line= 3
1468062.59826719430042.7520125351468061.36962292  430148.5636559
1468001.57811989  430339.4169403
#Sta/Elev= 30
 -103.35  519.78  -43.86  516.34       0  517.61   26.51     518   49.31   517.5
    55.2   517.5   64.95  517.93   77.51   517.5   83.04  517.74   85.24  517.53
   87.87     516   92.72   511.5   93.25     511  102.41   510.5  106.84   510.5
  108.25   511.5     127     525  129.33  524.85   131.6     526  134.94   526.5
  139.73   526.5  142.45  526.27  154.61  526.42  159.63  526.82  169.97  527.25
  172.53  527.07  176.08   526.5  177.36   526.5  187.29  527.47     200  528.03
#Mann= 8 ,-1,0
 -103.35     .03       0       0     .02       0   77.51     .12       0
   85.24     .06       0   92.72     .04       0  108.25     .06       0
     127     .12       0  139.73    .015       0
#XS Ineff= 1 ,-1
 -103.35   83.04     518
Permanent Ineff=
       F
Bank Sta=92.72,108.25
XS Rating Curve= 0 ,0
Exp/Cntr=0.3,0.1