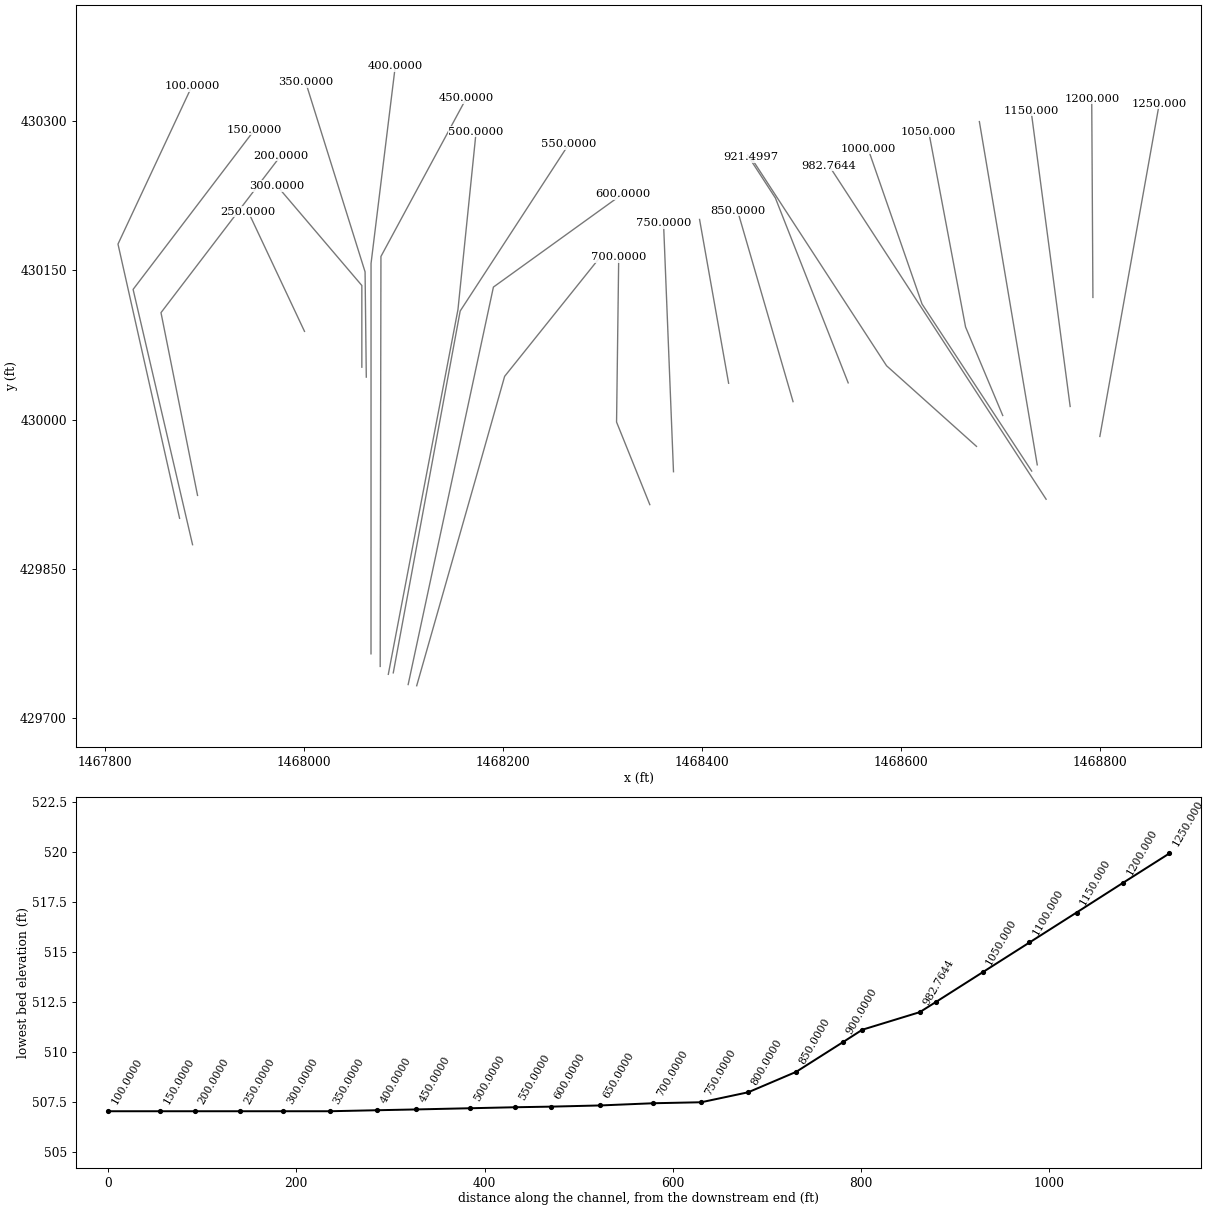
HEC-RAS study CLE-50-2.prj: CLE-50-2.25

--- CLE-50-2.g05 (geometry) ---

Geom Title=Full Rocl and Two Channel Add Depth Alt
Program Version=6.10
BEGIN GEOM DESCRIPTION:
Alternative with rock channel lining and excavation to 511.1 ft at bridge from XS 1250 to 100. Channel widening with two-step channel from XS 1250 to 100.
ODOT Mannings n:
Bare earth- 0.02
Rock Channel Protection- 0.4
Concrete- 0.015
HEC-RAS Manual Mannings n:
Natural Streams, 1. Minor Streams, b. Mountain streams, 1. Bottom: Gravels, cobbles and few
boulders- 0.040
Natural Streams, 2. Flood Plains, d. Trees, 1. Dense Willows, summer, straight- 0.120
Natural Streams, 2. Flood Plains, a. Pasture no brush, 1. short grass- 0.03
Natural Streams, 2. Flood Plains, c. Brush, 1. Scattered brush, heavy weeds- 0.05
Natural Streams, 2. Flood Plains, c. Brush, 3. Light brush and trees, in summer- 0.06
END GEOM DESCRIPTION:

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
River Reach=CLX_1           ,Reach

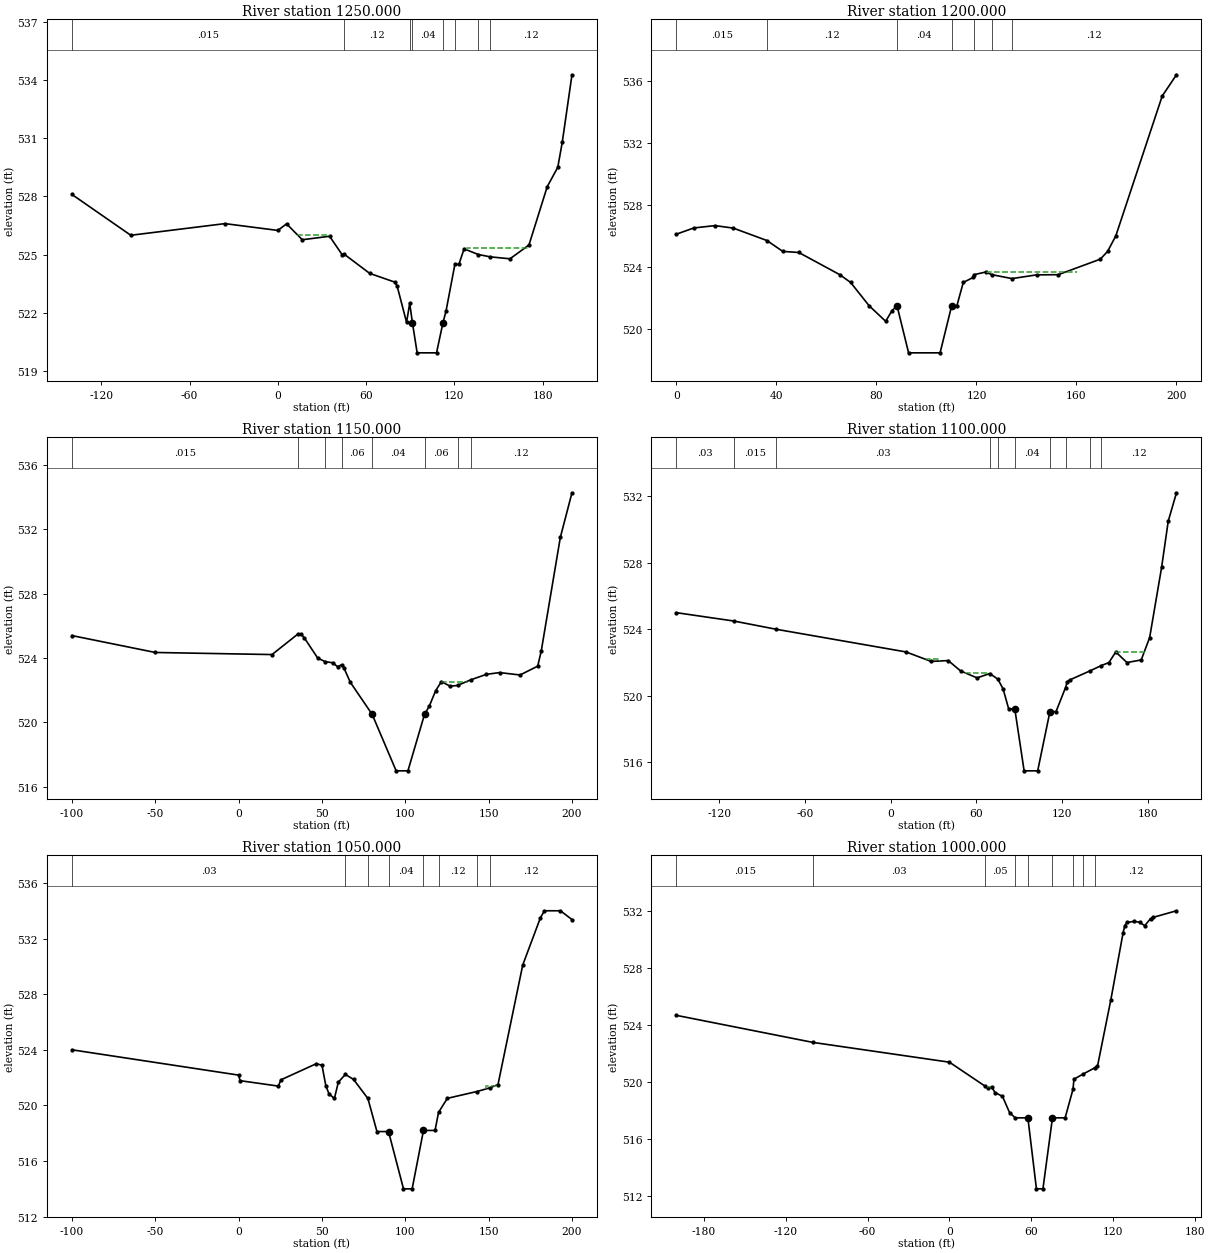
Type RM Length L Ch R = 1 ,1250.000,47.9,49.5,51.6
XS GIS Cut Line= 4
1468800.17590239429983.0629387161468807.20846646430022.439874131
1468824.78987661 430120.882212671468859.95269692 430317.76688975
#Sta/Elev= 30
    -140   528.1    -100     526     -36   526.6       0  526.25    5.93  526.59
    16.6  525.77   35.17  525.95   43.72     525   45.04  525.03   62.43  524.04
   79.48  523.59   81.06   523.4   87.52  521.52   89.66   522.5    91.5   521.5
   94.72  519.95   107.9  519.95  112.27   521.5  114.33  522.09  120.37   524.5
  123.08   524.5  126.64   525.3  136.37  525.01  144.41  524.89  157.86  524.79
  170.75   525.5  183.16   528.5  190.35   529.5  193.38  530.78     200  534.26
#Mann= 8 ,-1,0
    -140    .015       0   45.04     .12       0   89.66     .06       0
    91.5     .04       0  112.27     .06       0  120.37     .12       0
  136.37     .02       0  144.41     .12       0
#XS Ineff= 3 ,-1
    12.7   34.99     526   84.15   89.66   522.5  128.28  170.75  525.34
Permanent Ineff=
       F       F       F
Bank Sta=91.5,112.27
XS Rating Curve= 0 ,0
Exp/Cntr=0.3,0.1

Type RM Length L Ch R = 1 ,1200.000,50,49.1,50.7
XS GIS Cut Line= 2
1468793.21742771 430122.856109111468792.01050113  430322.8524674
#Sta/Elev= 30
       0  526.11    6.95  526.51   15.42  526.66   22.72   526.5   36.18   525.7
   42.52     525   48.93  524.93   65.35   523.5   69.67     523   77.07   521.5
   83.69   520.5   86.22  521.19   88.22   521.5   92.85  518.47  105.45  518.47
  110.08   521.5  112.17   521.5  114.72     523  118.73  523.33  118.95   523.5
  123.63  523.67   126.2   523.5  134.22  523.25  144.07  523.49   152.7   523.5
  169.53   524.5  172.45     525  175.74     526  194.29     535     200  536.37
#Mann= 7 ,-1,0
       0    .015       0   36.18     .12       0   88.22     .04       0
  110.08     .06       0  118.95     .12       0   126.2     .02       0
  134.22     .12       0
#XS Ineff= 2 ,-1
   77.07   88.22   521.5  124.38  160.11  523.67
Permanent Ineff=
       F       F
Bank Sta=88.22,110.08
XS Rating Curve= 0 ,0
Exp/Cntr=0.3,0.1

Type RM Length L Ch R = 1 ,1150.000,49.4,50,50
XS GIS Cut Line= 3
 1468770.3291533430013.2193880891468757.23592176 430112.35851905
1468731.04945867 430310.63678098
#Sta/Elev= 30
    -100   525.4     -50  524.35   20.02  524.22    35.6   525.5   37.42   525.5
    39.4  525.26   47.45     524   51.95  523.78   56.41  523.71   59.32  523.47
   61.77  523.58   63.11   523.4   66.98   522.5   80.12   520.5   94.51  516.99
  101.57  516.99  111.52   520.5  114.34     521  118.19  521.97  121.66  522.54
  126.93  522.25  131.34   522.3   139.3  522.65  148.67  522.99  156.59   523.1
  168.84  522.95  179.45   523.5  181.56  524.44     193   531.5     200  534.28
#Mann= 8 ,-1,0
    -100    .015       0    35.6     .03       0   51.95     .12       0
   61.77     .06       0   80.12     .04       0  111.52     .06       0
  131.34     .02       0   139.3     .12       0
#XS Ineff= 2 ,-1
                          121.69  137.66  522.54
Permanent Ineff=
       F       F
Bank Sta=80.12,111.52
XS Rating Curve= 0 ,0
Exp/Cntr=0.3,0.1

Type RM Length L Ch R = 1 ,1100.000,49.2,49.7,49.7
XS GIS Cut Line= 4
 1468737.2388876429954.5324565921468726.93071119430015.669527989
1468712.29975111  430102.44472611468679.04756912 430299.66108545
#Sta/Elev= 30
    -150     525    -110   524.5     -80     524   10.67  522.64   28.25  522.07
   40.25  522.12   48.86   521.5   60.39  521.08   69.34  521.34   75.02     521
   78.67  520.41   82.56  519.21   86.84  519.21   93.36  515.49  102.85  515.49
  111.42  519.05  115.69  519.05  122.36   520.5  123.59  520.85  125.14  520.95
  139.45   521.5  147.36  521.82  152.72     522  157.51  522.64  165.34     522
  175.33  522.16  181.22   523.5  189.59  527.72  194.23   530.5     200  532.21
#Mann= 10 ,-1,0
    -150     .03       0    -110    .015       0     -80     .03       0
   69.34     .12       0   75.02     .06       0   86.84     .04       0
  111.42     .06       0  122.36     .12       0  139.45     .02       0
  147.36     .12       0
#XS Ineff= 3 ,-1
   24.11    34.4  522.19   52.22   67.52  521.35  157.97   178.5  522.64
Permanent Ineff=
       F       F       F
Bank Sta=86.84,111.42
XS Rating Curve= 0 ,0
Exp/Cntr=0.3,0.1

Type RM Length L Ch R = 1 ,1050.000,48.2,49.7,51.3
XS GIS Cut Line= 3
1468702.53743758430004.1422907271468665.14676491 430093.15716821
1468628.07789209 430289.69189458
#Sta/Elev= 30
    -100     524       0  522.18     .87  521.78   23.85  521.39   25.35  521.84
   46.59     523      50  522.89   52.33  521.41   54.22  520.83   57.46   520.5
    59.8  521.67   64.05  522.23   68.93  521.87   77.55   520.5   82.98  518.12
   89.93  518.12   98.91     514   104.1     514   110.9   518.2  117.84   518.2
  119.94   519.5  125.23  520.51  142.96     521  150.91  521.27  155.61   521.5
  170.46   530.1  181.08   533.5  183.46     534  193.09     534     200  533.37
#Mann= 8 ,-1,0
    -100     .03       0   64.05     .12       0   77.55     .06       0
   89.93     .04       0   110.9     .06       0  119.94     .12       0
  142.96     .02       0  150.91     .12       0
#XS Ineff= 3 ,-1
     -50   46.59     523      50   64.05  522.23  148.48     155  521.37
Permanent Ineff=
       F       F       F
Bank Sta=89.93,110.9
XS Rating Curve= 0 ,0
Exp/Cntr=0.3,0.1

Type RM Length L Ch R = 1 ,1000.000,14.8,17.2,20.6
XS GIS Cut Line= 3
1468731.62975802429948.2758093491468621.38432022430116.251121665
1468567.12800099 430272.39077914
#Sta/Elev= 30
    -200   524.7    -100   522.8       0  521.41   25.75  519.75   28.29  519.59
   31.05  519.65   33.37  519.28   38.85  519.01   44.11  517.86    48.2   517.5
   57.48   517.5   63.75  512.51   68.51  512.51    75.5   517.5   84.78   517.5
   90.51   519.5   91.26  520.22   98.22  520.59  106.59  521.02  108.47  521.12
  118.28   525.8  127.23   530.5  128.48     531  129.97  531.23  135.12   531.3
   139.3  531.25  143.06     531  147.37   531.5  149.35  531.59  166.35  532.05
#Mann= 9 ,-1,0
    -200    .015       0    -100     .03       0   25.75     .05       0
    48.2     .06       0   57.48     .04       0    75.5     .06       0
   90.51     .12       0   98.22     .02       0  106.59     .12       0
#XS Ineff= 1 ,-1
   27.34   30.24  519.66
Permanent Ineff=
       F
Bank Sta=57.48,75.5
XS Rating Curve= 0 ,0
Exp/Cntr=0.5,0.3

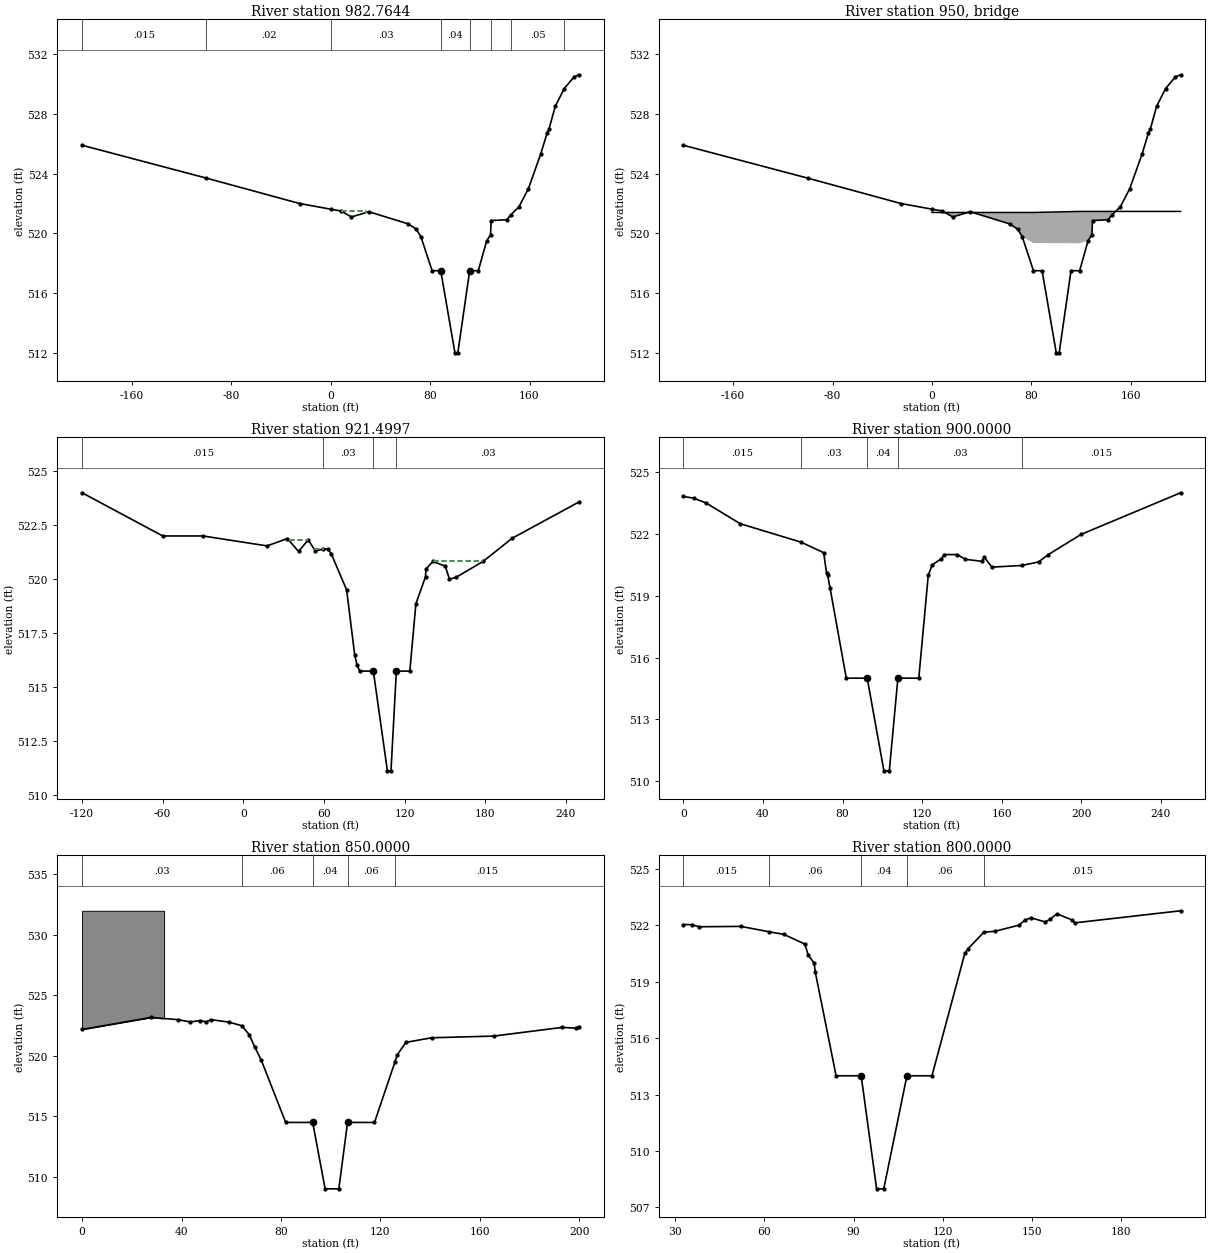
Type RM Length L Ch R = 1 ,982.7644,62.7,61,60.7
XS GIS Cut Line= 3
1468746.14501959429919.9584453481468637.05306538 430087.58584623
1468527.96111117 430255.21324711
#Sta/Elev= 30
    -200   525.9    -100   523.7     -25     522       0  521.62    8.24   521.5
   16.72   521.1   30.75  521.45   62.62  520.63   68.89  520.28   72.61  519.78
   81.62   517.5   88.57   517.5     100     512  102.33     512  111.85   517.5
   118.8   517.5  125.54   519.5  128.66  519.91  129.15  520.86  141.61  520.91
   145.2  521.26  151.56  521.78  159.15     523  169.09  525.33  174.16  526.72
   175.6  526.96  180.68   528.5   187.9  529.69  195.84  530.48     200  530.62
#Mann= 8 ,-1,0
    -200    .015       0    -100     .02       0       0     .03       0
   88.57     .04       0  111.85     .03       0  129.15     .02       0
   145.2     .05       0   187.9     .02       0
#XS Ineff= 1 ,-1
    8.24   28.34  521.47
Permanent Ineff=
       F
Bank Sta=88.57,111.85
XS Rating Curve= 0 ,0
Exp/Cntr=0.5,0.3

Type RM Length L Ch R = 3 ,950     ,,,
Bridge Culvert--1,0,-1,-1, 0
Deck Dist Width WeirC Skew NumUp NumDn MinLoCord MaxHiCord MaxSubmerge Is_Ogee
11.3,36,2.6,0, 4, 4, , , 0.98, 0, 0,0,,
       0   81.62   118.8     200
   521.4   521.4  521.47  521.47
  519.35  519.35  519.34  519.34
       0   86.75  123.93     200
   519.3   519.3  519.43  519.43
  517.21  517.21   517.3   517.3
BR Coef= 1 , 1 , 0 ,, 0 ,,,0.8,0,1.2,0,
WSPro=,,,, 1 ,,,, 0 ,,,, 0 ,,,,-1 ,-1 ,-1 , 0 , 0 , 0 , 0 , 0
BC Design=,, 0 ,, 0 ,,,,,,
BC Use User HTab Curves=0
BC User HTab FreeFlow(D)= 0

Type RM Length L Ch R = 1 ,921.4997,22.4,20.5,19.3
XS GIS Cut Line= 5
1468676.14883567429973.0940408371468661.25635643429986.443724806
1468585.70485838 430054.168420341468476.61290417 430221.79582122
1468449.33991562 430263.70267144
#Sta/Elev= 30
    -120     524     -60     522     -30     522    17.6  521.54   32.87  521.88
    41.1  521.28   48.31  521.82   53.66   521.3   59.51   521.4   62.88  521.39
   65.41  521.18    76.9   519.5   82.88   516.5   84.69     516   86.75  515.74
   96.77  515.74  107.22  511.12  109.91  511.12  113.91  515.74  123.93  515.74
  128.44  518.86  135.61  520.11  135.92  520.46  141.05  520.82  150.31   520.6
  153.43     520   158.5  520.09  178.45  520.82     200  521.89     250  523.58
#Mann= 4 ,-1,0
    -120    .015       0   59.51     .03       0   96.77     .04       0
  113.91     .03       0
#XS Ineff= 4 ,-1
     -30   32.87  521.88    33.9    48.2  521.82   52.48   60.36  521.41
  141.61  178.45  520.82
Permanent Ineff=
       F       F       F       F
Bank Sta=96.77,113.91
XS Rating Curve= 0 ,0
Exp/Cntr=0.5,0.3

Type RM Length L Ch R = 1 ,900.0000,49.8,49.8,49.8
XS GIS Cut Line= 3
1468547.13385365 430036.952217391468473.94643698430222.823006603
1468445.92329937430265.994281878
#Sta/Elev= 29
       0  523.82    5.07  523.74   11.47   523.5   28.52   522.5   59.24   521.6
   70.54  521.09   71.98   520.1   72.52     520   73.69   519.4    81.9     515
   92.42     515  100.82   510.5  103.54   510.5  107.85     515  118.36     515
  123.13     520  125.13   520.5  129.72   520.8  131.26     521  137.66     521
  141.84  520.77  150.17  520.67  151.24  520.88   155.1  520.39  170.07  520.47
  178.57  520.64  183.51     521     200  521.98     250     524
#Mann= 5 ,-1,0
       0    .015       0   59.24     .03       0   92.42     .04       0
  107.85     .03       0  170.07    .015       0
#XS Ineff= 1 ,-1
  137.66  183.51     521
Permanent Ineff=
       F
Bank Sta=92.42,107.85
XS Rating Curve= 0 ,0
Exp/Cntr=0.3,0.1

Type RM Length L Ch R = 1 ,850.0000,51.1,50.8,49.2
XS GIS Cut Line= 2
1468491.68972291 430018.089518641468435.89246107 430210.14853449
#Sta/Elev= 26
       0  522.19    27.7  523.18   38.51     523   43.52  522.81   47.48  522.92
   49.97  522.82   51.78     523   58.93   522.8    64.2   522.5    67.2  521.77
    69.5  520.72   72.01  519.69   81.92   514.5   92.77   514.5   97.78  509.01
  103.29  509.01   106.8   514.5  117.64   514.5  125.86   519.5  126.84   520.1
  130.25  521.12  140.62   521.5  165.62  521.64  193.18  522.36  198.69  522.29
     200  522.43
#Mann= 5 ,-1,0
       0     .03       0    64.2     .06       0   92.77     .04       0
   106.8     .06       0  125.86    .015       0
#Block Obstruct= 1 ,-1
       0      33     532
Bank Sta=92.77,106.8
XS Rating Curve= 0 ,0
Exp/Cntr=0.3,0.1

Type RM Length L Ch R = 1 ,800.0000,50.5,49.9,48.5
XS GIS Cut Line= 2
1468426.90854645430036.5671496951468397.70031941  430201.2672788
#Sta/Elev= 29
   32.73  522.04   35.48  522.03   38.02  521.92   52.08  521.94   61.66  521.65
   66.44  521.52   73.61     521   74.71  520.42   76.69     520   77.11   519.5
    84.1     514   92.54     514   97.73  507.99  100.14  507.99  107.93     514
  116.36     514   127.4   520.5  128.56  520.76   133.8  521.63   137.5  521.68
  145.53     522  147.65  522.27  149.62   522.4  154.41  522.18  156.06  522.31
  158.35  522.61  163.39  522.29   164.5  522.13     200  522.77
#Mann= 5 ,-1,0
   32.73    .015       0   61.66     .06       0   92.54     .04       0
  107.93     .06       0   133.8    .015       0
Bank Sta=92.54,107.93
XS Rating Curve= 0 ,0
Exp/Cntr=0.3,0.1

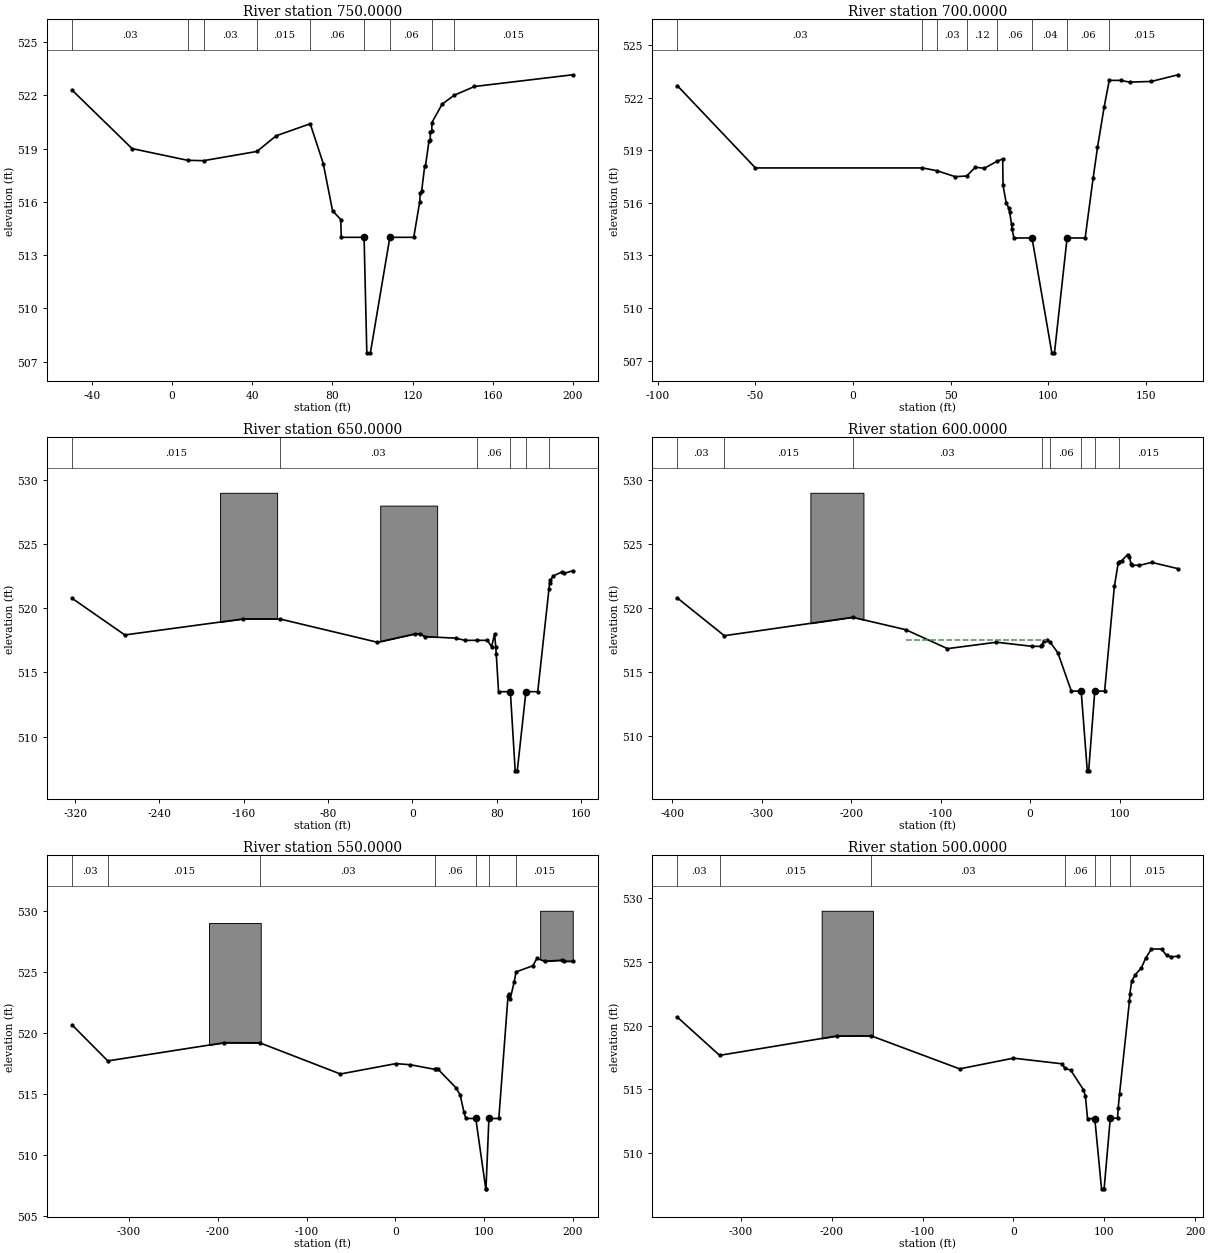
Type RM Length L Ch R = 1 ,750.0000,51,50.9,50.5
XS GIS Cut Line= 3
1468371.48612002 429947.609549891468369.48537408 429997.56950401
1468361.48239031 430197.40932049
#Sta/Elev= 30
     -50   522.3     -20     519    7.72  518.34   15.73  518.32   42.33  518.84
    51.9  519.72   68.93   520.4   75.43  518.16   80.08   515.5    84.2     515
   84.41     514   95.82     514   97.19  507.49   98.97  507.49  108.69     514
  120.62     514  123.59     516  123.88   516.5  124.56516.6009  126.07     518
  126.48  518.03  128.22  519.42  128.82   519.5  128.95  519.96  129.64     520
  129.68  520.47  134.78   521.5   140.7     522  150.94   522.5     200  523.16
#Mann= 9 ,-1,0
     -50     .03       0    7.72     .02       0   15.73     .03       0
   42.33    .015       0   68.93     .06       0   95.82     .04       0
  108.69     .06       0  129.68     .12       0   140.7    .015       0
Bank Sta=95.82,108.69
XS Rating Curve= 0 ,0
Exp/Cntr=0.3,0.1

Type RM Length L Ch R = 1 ,700.0000,62.2,56.4,51.2
XS GIS Cut Line= 3
1468347.67182205 429914.50974402 1468314.2359719 429997.53869117
1468316.40262427430163.201654615
#Sta/Elev= 30
     -90   522.7     -50     518   35.52     518   43.01  517.84   52.26   517.5
   58.15  517.54   62.65  518.04   67.18  517.98    73.9  518.39   76.61  518.51
   76.79     517   78.42     516   79.61  515.74   80.12   515.5   81.13   514.8
    81.4   514.5   82.38     514   91.63     514  101.78  507.44  103.13  507.44
  109.59     514  118.84     514  122.92  517.42  125.16  519.17   128.6   521.5
  131.19     523  137.07     523  141.58   522.9  152.77  522.94   166.4  523.32
#Mann= 8 ,-1,0
     -90     .03       0   35.52     .02       0   43.01     .03       0
   58.15     .12       0    73.9     .06       0   91.63     .04       0
  109.59     .06       0  131.19    .015       0
#XS Ineff= 1 ,-1
     -90   76.61  518.51
Permanent Ineff=
       F
Bank Sta=91.63,109.59
XS Rating Curve= 0 ,0
Exp/Cntr=0.3,0.1

Type RM Length L Ch R = 1 ,650.0000,54.9,52.4,51.4
XS GIS Cut Line= 4
1468113.27637661429732.4024439161468172.87876954429941.595156356
1468201.69242222 430043.499807181468297.92692726 430163.64328688
#Sta/Elev= 29
 -322.93  520.78 -272.84  517.92 -160.49  519.17 -125.99  519.17  -33.26  517.35
    2.19     518    6.97     518   11.81  517.79   40.87  517.67   49.78   517.5
   60.79   517.5   71.04   517.5   75.01     517   77.86     518   78.95     517
   79.46  516.42   81.63   513.5   92.84   513.5    97.4  507.33   99.38  507.33
   107.6   513.5  118.81   513.5  129.45   521.5  130.12     522  130.81  522.19
  133.64  522.53  141.74  522.82  144.16  522.73     152  522.92
#Mann= 6 ,-1,0
 -322.93    .015       0 -125.99     .03       0   60.79     .06       0
   92.84     .04       0   107.6     .06       0  129.45    .015       0
#XS Ineff= 2 ,-1
 -322.93 -160.49  519.17 -125.99   77.86     518
Permanent Ineff=
       F       F
#Block Obstruct= 2 ,-1
  -182.5  -128.4     529   -30.6    23.4     528
Bank Sta=92.84,107.6
XS Rating Curve= 0 ,0
Exp/Cntr=0.3,0.1

Type RM Length L Ch R = 1 ,600.0000,35,37.9,40.1
XS GIS Cut Line= 3
1468104.69286019429733.6207019661468190.40888511430133.257753229
1468320.13174031430226.751702923
#Sta/Elev= 30
 -394.33  520.78 -341.77  517.83 -198.25  519.27    -139   518.3  -92.39  516.82
  -37.61  517.32    2.39     517   11.88     517   12.79  517.12   15.51   517.4
   18.38  517.52   22.53  517.31   30.91   516.5   46.04   513.5   57.03   513.5
   63.86  507.27    65.4  507.27   72.23   513.5   83.22   513.5   94.11  521.68
   98.43   523.5   98.98  523.62  102.46   523.7  108.87  524.17  110.38     524
  113.22   523.4  114.36  523.34  122.13  523.33  135.85  523.56  165.28  523.07
#Mann= 8 ,-1,0
 -394.33     .03       0 -341.77    .015       0 -198.25     .03       0
   12.79     .12       0   22.53     .06       0   57.03     .04       0
   72.23     .06       0   98.98    .015       0
#XS Ineff= 2 ,-1
 -394.33 -198.25  519.27    -139   19.08  517.53
Permanent Ineff=
       F       F
#Block Obstruct= 1 ,-1
  -245.6  -186.3     529
Bank Sta=57.03,72.23
XS Rating Curve= 0 ,0
Exp/Cntr=0.3,0.1

Type RM Length L Ch R = 1 ,550.0000,44,47.8,51.8
XS GIS Cut Line= 3
1468089.71680587429745.3686937781468157.00660937  430109.2092995
1468266.14806495 430276.80447447
#Sta/Elev= 30
 -364.26  520.66 -323.94  517.71 -192.89   519.2 -152.56  519.19  -61.83  516.64
     .66  517.49   16.78   517.4   44.64  517.02   46.28  517.09   48.23  517.03
   68.53   515.5   73.12  514.93   77.46   513.5   79.53     513   90.72     513
  102.01  507.24  102.24  507.24  105.53     513  116.71     513  127.05     523
  127.85  523.17  129.49  522.75  133.98  524.18  136.19     525  155.02   525.5
  159.66   526.1  168.39  525.87  187.56  525.95  189.89  525.87     200  525.86
#Mann= 7 ,-1,0
 -364.26     .03       0 -323.94    .015       0 -152.56     .03       0
   44.64     .06       0   90.72     .04       0  105.53     .06       0
  136.19    .015       0
#XS Ineff= 2 ,-1
 -364.26 -192.89   519.2 -152.56     .66  517.49
Permanent Ineff=
       F       F
#Block Obstruct= 2 ,-1
  -209.9  -151.6     529   163.3     200     530
Bank Sta=90.72,105.53
XS Rating Curve= 0 ,0
Exp/Cntr=0.3,0.1

Type RM Length L Ch R = 1 ,500.0000,60.7,57.3,53.5
XS GIS Cut Line= 3
1468084.73336115429743.8986369651468154.77759391 430110.72345484
1468173.05097918430289.673024693
#Sta/Elev= 30
    -370  520.66 -323.46  517.66 -194.44  519.18 -156.57  519.19  -59.26   516.6
       0  517.44   53.15     517   56.83  516.64   62.99   516.5      77  514.97
   79.14   514.5   81.56   512.7   89.53   512.7   96.95  507.19    99.8  507.19
  106.59  512.73  114.56  512.73  115.35  513.56  116.73  514.62  127.72  521.94
  128.16   522.5   130.2   523.5  134.23     524  140.63   524.5  145.43  525.26
  151.76     526     163     526  168.47   525.5  173.81  525.39  181.16  525.44
#Mann= 7 ,-1,0
    -370     .03       0 -323.46    .015       0 -156.57     .03       0
   56.83     .06       0   89.53     .04       0  106.59     .06       0
  128.16    .015       0
#XS Ineff= 3 ,-1
                            -370 -156.57  519.19 -156.57       0  517.44
Permanent Ineff=
       F       F       F
#Block Obstruct= 1 ,-1
  -211.1  -154.7     529
Bank Sta=89.53,106.59
XS Rating Curve= 0 ,0
Exp/Cntr=0.3,0.1

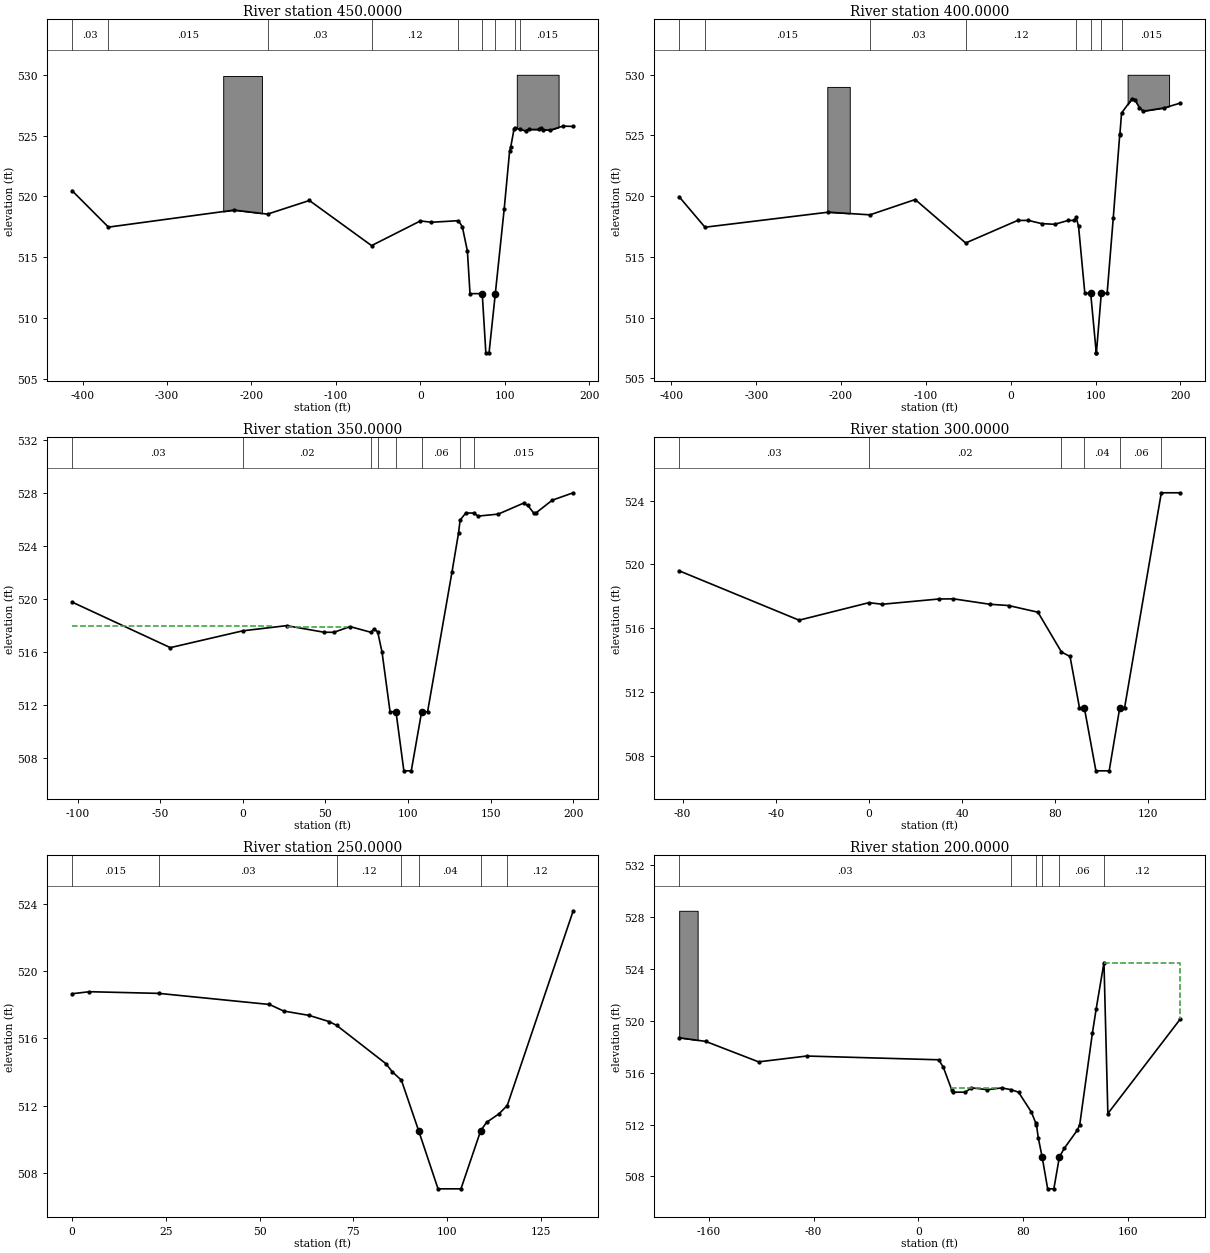
Type RM Length L Ch R = 1 ,450.0000,38.9,41.8,44.8
XS GIS Cut Line= 3
1468076.57499801429751.8331059291468077.32314336430164.061194277
1468163.15318918 430323.11235073
#Sta/Elev= 30
 -412.47  520.47 -369.37  517.47 -220.68  518.87 -181.03  518.54 -131.46  519.66
  -57.82  515.95       0  517.98    13.1  517.87   45.03     518   49.61   517.5
   55.62   515.5   58.72     512   73.19     512   77.47  507.13   81.26  507.13
   88.67     512   99.22  518.98  105.62  523.73  106.94  524.06  110.73   525.5
  111.57  525.66  118.13   525.5   124.5  525.39  128.03   525.5  140.85   525.5
  142.71  525.63  144.99  525.49   153.4  525.44  168.75  525.78  180.92  525.75
#Mann= 9 ,-1,0
 -412.47     .03       0 -369.37    .015       0 -181.03     .03       0
  -57.82     .12       0   45.03     .06       0   73.19     .04       0
   88.67     .06       0  111.57     .12       0  118.13    .015       0
#XS Ineff= 1 ,-1
 -412.47 -131.46  519.66
Permanent Ineff=
       F
#Block Obstruct= 2 ,-1
  -233.5  -187.6   529.9   114.1   163.6     530
Bank Sta=73.19,88.67
XS Rating Curve= 0 ,0
Exp/Cntr=0.3,0.1

Type RM Length L Ch R = 1 ,400.0000,46.2,50,52.5
XS GIS Cut Line= 3
1468067.33442339429764.5123954591468067.37900316 430157.09751214
1468091.76949029 430355.60470127
#Sta/Elev= 30
 -390.81  519.95 -360.39  517.44 -214.92  518.68 -165.95  518.46 -112.57  519.72
  -53.09  516.14    8.21     518    20.9     518   36.37  517.74    51.7  517.68
   67.87     518   74.76     518   77.21  518.25   80.01   517.5   87.39     512
   94.28     512  100.87  507.09  101.06  507.09  106.81     512   113.7     512
   120.9   518.2  128.46     525  128.78  525.14  130.69  526.85  143.14  528.03
  146.29  527.96  151.65  527.29  156.17     527  180.93  527.27     200  527.67
#Mann= 8 ,-1,0
 -390.81     .03       0 -360.39    .015       0 -165.95     .03       0
  -53.09     .12       0   77.21     .06       0   94.28     .04       0
  106.81     .06       0  130.69    .015       0
#XS Ineff= 1 ,-1
 -112.57   77.21  518.25
Permanent Ineff=
       F
#Block Obstruct= 2 ,-1
  -216.2  -189.7     529   137.8   186.7     530
Bank Sta=94.28,106.81
XS Rating Curve= 0 ,0
Exp/Cntr=0.3,0.1

Type RM Length L Ch R = 1 ,350.0000,46.7,49.3,52.2
XS GIS Cut Line= 3
1468062.59826719430042.7520125351468061.36962292  430148.5636559
1468001.57811989  430339.4169403
#Sta/Elev= 30
 -103.35  519.78  -43.86  516.34       0  517.61   26.51     518   49.31   517.5
    55.2   517.5   64.95  517.93   77.51   517.5   79.45  517.74   81.65  517.53
   84.28     516   89.13   511.5   92.72   511.5    97.5  507.04  101.97  507.04
  108.25   511.5  111.84   511.5  126.65  522.07  130.59     525  131.54  525.97
  134.94   526.5  139.73   526.5  142.45  526.27  154.61  526.42  169.97  527.25
  172.53  527.07  176.08   526.5  177.36   526.5  187.29  527.47     200  528.03
#Mann= 8 ,-1,0
 -103.35     .03       0       0     .02       0   77.51     .12       0
   81.65     .06       0   92.72     .04       0  108.25     .06       0
  131.54     .12       0  139.73    .015       0
#XS Ineff= 3 ,-1
 -103.35   18.47     518   26.51   63.37  517.91   69.67   79.45  517.74
Permanent Ineff=
       F       F       F
Bank Sta=92.72,108.25
XS Rating Curve= 0 ,0
Exp/Cntr=0.3,0.1

Type RM Length L Ch R = 1 ,300.0000,51.1,45.7,45.3
XS GIS Cut Line= 3
1468058.11406649430052.7078346611468058.11406649 430134.86339744
1467972.90442139430234.971812253
#Sta/Elev= 19
   -81.5   519.6     -30   516.5       0   517.6    5.68   517.5   29.99  517.83
   36.32  517.84   51.88   517.5   59.97  517.42    72.6     517    82.7   514.5
   86.38  514.22   90.43     511   92.52     511   97.49  507.04  103.19  507.04
  107.73     511  109.81     511  125.58   524.5  133.76   524.5
#Mann= 6 ,-1,0
   -81.5     .03       0       0     .02       0    82.7     .06       0
   92.52     .04       0  107.73     .06       0  125.58     .12       0
Bank Sta=92.52,107.73
XS Rating Curve= 0 ,0
Exp/Cntr=0.3,0.1

Type RM Length L Ch R = 1 ,250.0000,59.4,48.4,44.9
XS GIS Cut Line= 2
1468000.46513742   430088.7361661467943.77037464430209.249030465
#Sta/Elev= 19
       0  518.66    4.64  518.78   23.17  518.68   52.65  518.02   56.42  517.63
   63.21  517.37   68.56     517   70.53  516.78   83.66   514.5   85.45     514
   87.83  513.51   92.43   510.5    97.6  507.04  103.71  507.04  108.97   510.5
  110.54     511  113.81   511.5  116.05     512  133.65   523.6
#Mann= 7 ,-1,0
       0    .015       0   23.17     .03       0   70.53     .12       0
   87.83     .06       0   92.43     .04       0  108.97     .06       0
  116.05     .12       0
Bank Sta=92.43,108.97
XS Rating Curve= 0 ,0
Exp/Cntr=0.3,0.1

Type RM Length L Ch R = 1 ,200.0000,37,36.9,38.2
XS GIS Cut Line= 4
1467892.91662702429923.8038567251467892.39692046429926.402389531
1467856.16801496430107.5469170631467976.54147519430265.317957172
#Sta/Elev= 30
 -182.65   518.7 -162.44  518.42    -122  516.84  -85.29  517.29   15.52     517
   19.01  516.43   25.63  514.63   26.47   514.5   35.79   514.5   40.52  514.84
   52.69  514.69   63.58  514.83   70.84  514.69   76.46   514.5   86.22  512.97
   89.67   512.1   90.13     512   91.48     511   94.48   509.5    98.7  507.04
  103.42  507.04  107.64   509.5  111.34  510.16  121.41  511.58  123.19     512
  132.89  519.09  135.72  520.92  141.68   524.5  144.65  512.85     200  520.15
#Mann= 6 ,-1,0
 -182.65     .03       0   70.84     .12       0   89.67     .06       0
   94.48     .04       0  107.64     .06       0  141.68     .12       0
#XS Ineff= 2 ,-1
   24.84   60.23  514.83  141.68     200   524.5
Permanent Ineff=
       F       F
#Block Obstruct= 1 ,-1
 -182.65 -168.55   528.5
Bank Sta=94.48,107.64
XS Rating Curve= 0 ,0
Exp/Cntr=0.3,0.1

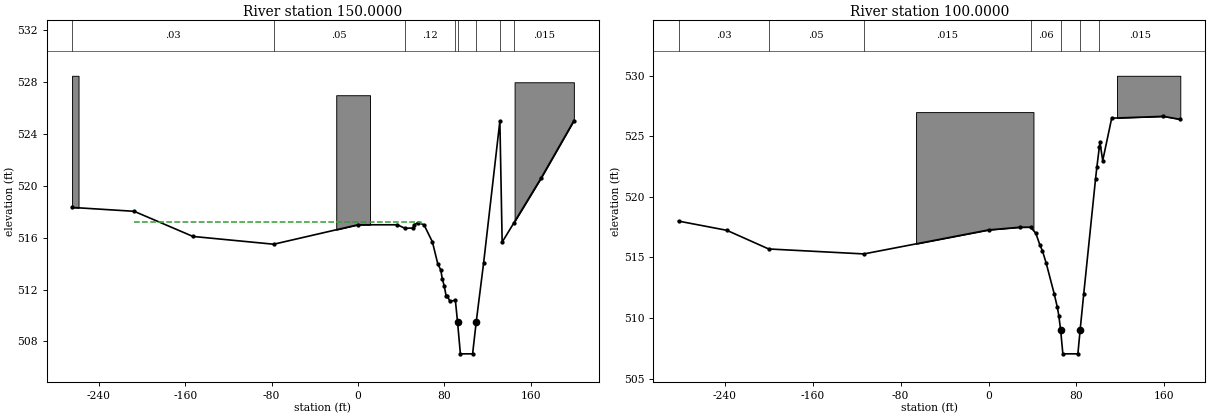
Type RM Length L Ch R = 1 ,150.0000,53.3,55.4,57.6
XS GIS Cut Line= 3
1467887.91071052429874.2319693451467828.11983005430130.920404487
1467950.34168815 430291.53265049
#Sta/Elev= 30
 -264.77  518.34 -207.27  518.04 -152.81   516.1     -78   515.5       0     517
   36.59     517   43.51  516.73   51.01  516.75   52.22     517   55.64  517.17
   61.19     517   68.97  515.68   73.93     514   76.78   513.5   78.07  512.85
   79.85  512.31   81.68  511.52   82.96   511.5   85.08   511.1   90.25  511.17
   92.26   509.5    94.9  507.04  106.22  507.04  109.56   509.5  116.39  514.04
  131.47     525  133.59  515.66  144.38  517.14  169.82  520.63     200  525.03
#Mann= 8 ,-1,0
 -264.77     .03       0     -78     .05       0   43.51     .12       0
   90.25     .06       0   92.26     .04       0  109.56     .06       0
  131.47     .12       0  144.38    .015       0
#XS Ineff= 2 ,-1
 -207.27   57.97  517.18  131.47     200     525
Permanent Ineff=
       F       F
#Block Obstruct= 3 ,-1
 -264.77 -258.77   528.5   -20.1    11.2     527   145.1     200     528
Bank Sta=92.26,109.56
XS Rating Curve= 0 ,0
Exp/Cntr=0.3,0.1

Type RM Length L Ch R = 1 ,100.0000,52.1,56.8,62.4
XS GIS Cut Line= 3
 1467874.8644403429900.7774779571467812.92706322430176.498704963
 1467887.2931541 430335.39353907
#Sta/Elev= 27
    -282     518 -238.08  517.24    -200   515.7  -113.4  515.29       0  517.27
   28.21  517.49   38.27   517.5   43.03     517   46.87     516   49.06  515.55
   52.58   514.5   59.76     512   62.65  510.88      64  510.17   65.63     509
   67.65  507.04   81.32  507.04   83.35     509   86.66     512    97.4   521.5
   98.59  522.46  100.85  524.12  101.38   524.5  103.92     523  112.08   526.5
   159.2  526.65  174.52   526.4
#Mann= 7 ,-1,0
    -282     .03       0    -200     .05       0  -113.4    .015       0
   38.27     .06       0   65.63     .04       0   83.35     .06       0
  100.85    .015       0
#XS Ineff= 1 ,-1
    -282   38.27   517.5
Permanent Ineff=
       F
#Block Obstruct= 2 ,-1
   -65.9    40.9     527   116.9   174.5     530
Bank Sta=65.63,83.35
XS Rating Curve= 0 ,0
Exp/Cntr=0.3,0.1

--- CLE-50-2.g06 (geometry) ---

Geom Title=Full Rock Excavation Add Depth Alt
Program Version=6.10
BEGIN GEOM DESCRIPTION:
Alternative with rock channel lining and excavation to 511.1 ft at bridge from XS 1250 to 100. Channel widening l from XS 1250 to 100.
ODOT Mannings n:
Bare earth- 0.02
Rock Channel Protection- 0.4
Concrete- 0.015
HEC-RAS Manual Mannings n:
Natural Streams, 1. Minor Streams, b. Mountain streams, 1. Bottom: Gravels, cobbles and few
boulders- 0.040
Natural Streams, 2. Flood Plains, d. Trees, 1. Dense Willows, summer, straight- 0.120
Natural Streams, 2. Flood Plains, a. Pasture no brush, 1. short grass- 0.03
Natural Streams, 2. Flood Plains, c. Brush, 1. Scattered brush, heavy weeds- 0.05
Natural Streams, 2. Flood Plains, c. Brush, 3. Light brush and trees, in summer- 0.06
END GEOM DESCRIPTION:

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
River Reach=CLX_1           ,Reach

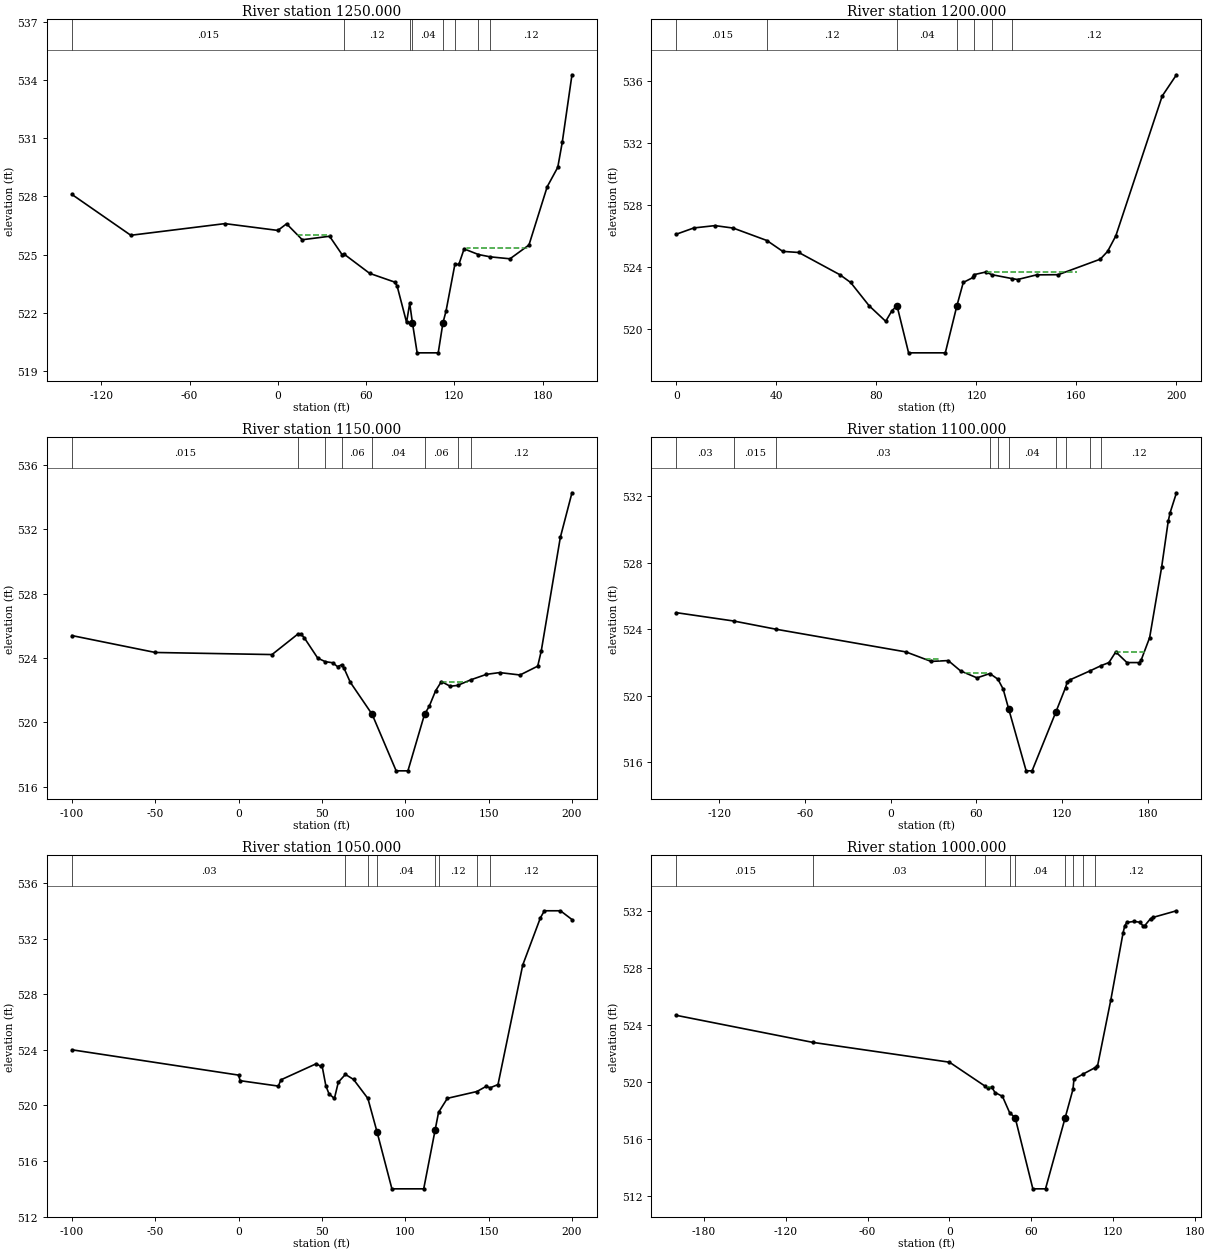
Type RM Length L Ch R = 1 ,1250.000,47.9,49.5,51.6
XS GIS Cut Line= 4
1468800.17590239429983.0629387161468807.20846646430022.439874131
1468824.78987661 430120.882212671468859.95269692 430317.76688975
#Sta/Elev= 30
    -140   528.1    -100     526     -36   526.6       0  526.25    5.93  526.59
    16.6  525.77   35.17  525.95   43.72     525   45.04  525.03   62.43  524.04
   79.48  523.59   81.06   523.4   87.52  521.52   89.66   522.5    91.5   521.5
   94.72  519.95  109.05  519.95  112.27   521.5  114.33  522.09  120.37   524.5
  123.08   524.5  126.64   525.3  136.37  525.01  144.41  524.89  157.86  524.79
  170.75   525.5  183.16   528.5  190.35   529.5  193.38  530.78     200  534.26
#Mann= 8 ,-1,0
    -140    .015       0   45.04     .12       0   89.66     .06       0
    91.5     .04       0  112.27     .06       0  120.37     .12       0
  136.37     .02       0  144.41     .12       0
#XS Ineff= 3 ,-1
    12.7   34.99     526   84.15   89.66   522.5  128.28  170.75  525.34
Permanent Ineff=
       F       F       F
Bank Sta=91.5,112.27
XS Rating Curve= 0 ,0
Exp/Cntr=0.3,0.1

Type RM Length L Ch R = 1 ,1200.000,50,49.1,50.7
XS GIS Cut Line= 2
1468793.21742771 430122.856109111468792.01050113  430322.8524674
#Sta/Elev= 30
       0  526.11    6.95  526.51   15.42  526.66   22.72   526.5   36.18   525.7
   42.52     525   48.93  524.93   65.35   523.5   69.67     523   77.07   521.5
   83.69   520.5   86.22  521.19   88.22   521.5   92.85  518.47  107.54  518.47
  112.17   521.5  114.72     523  118.73  523.33  118.95   523.5  123.63  523.67
   126.2   523.5  134.22  523.25  136.46  523.19  144.07  523.49   152.7   523.5
  169.53   524.5  172.45     525  175.74     526  194.29     535     200  536.37
#Mann= 7 ,-1,0
       0    .015       0   36.18     .12       0   88.22     .04       0
  112.17     .06       0  118.95     .12       0   126.2     .02       0
  134.22     .12       0
#XS Ineff= 2 ,-1
   77.07   88.22   521.5  124.38  160.11  523.67
Permanent Ineff=
       F       F
Bank Sta=88.22,112.17
XS Rating Curve= 0 ,0
Exp/Cntr=0.3,0.1

Type RM Length L Ch R = 1 ,1150.000,49.4,50,50
XS GIS Cut Line= 3
 1468770.3291533430013.2193880891468757.23592176 430112.35851905
1468731.04945867 430310.63678098
#Sta/Elev= 30
    -100   525.4     -50  524.35   20.02  524.22    35.6   525.5   37.42   525.5
    39.4  525.26   47.45     524   51.95  523.78   56.41  523.71   59.32  523.47
   61.77  523.58   63.11   523.4   66.98   522.5   80.12   520.5   94.51  516.99
  101.57  516.99  111.52   520.5  114.34     521  118.19  521.97  121.66  522.54
  126.93  522.25  131.34   522.3   139.3  522.65  148.67  522.99  156.59   523.1
  168.84  522.95  179.45   523.5  181.56  524.44     193   531.5     200  534.28
#Mann= 8 ,-1,0
    -100    .015       0    35.6     .03       0   51.95     .12       0
   61.77     .06       0   80.12     .04       0  111.52     .06       0
  131.34     .02       0   139.3     .12       0
#XS Ineff= 2 ,-1
                          121.69  137.66  522.54
Permanent Ineff=
       F       F
Bank Sta=80.12,111.52
XS Rating Curve= 0 ,0
Exp/Cntr=0.3,0.1

Type RM Length L Ch R = 1 ,1100.000,49.2,49.7,49.7
XS GIS Cut Line= 4
 1468737.2388876429954.5324565921468726.93071119430015.669527989
1468712.29975111  430102.44472611468679.04756912 430299.66108545
#Sta/Elev= 30
    -150     525    -110   524.5     -80     524   10.67  522.64   28.25  522.07
   40.25  522.12   48.86   521.5   60.39  521.08   69.34  521.34   75.02     521
   78.67  520.41   82.56  519.21   94.78  515.49   98.93  515.49  115.69  519.05
  122.36   520.5  123.59  520.85  125.14  520.95  139.45   521.5  147.36  521.82
  152.72     522  157.51  522.64  165.34     522  174.08     522  175.33  522.16
  181.22   523.5  189.59  527.72  194.23   530.5  195.51     531     200  532.21
#Mann= 10 ,-1,0
    -150     .03       0    -110    .015       0     -80     .03       0
   69.34     .12       0   75.02     .06       0   82.56     .04       0
  115.69     .06       0  122.36     .12       0  139.45     .02       0
  147.36     .12       0
#XS Ineff= 3 ,-1
   24.11    34.4  522.19   52.22   67.52  521.35  157.97   178.5  522.64
Permanent Ineff=
       F       F       F
Bank Sta=82.56,115.69
XS Rating Curve= 0 ,0
Exp/Cntr=0.3,0.1

Type RM Length L Ch R = 1 ,1050.000,48.2,49.7,51.3
XS GIS Cut Line= 3
1468702.53743758430004.1422907271468665.14676491 430093.15716821
1468628.07789209 430289.69189458
#Sta/Elev= 30
    -100     524       0  522.18     .87  521.78   23.85  521.39   25.35  521.84
   46.59     523   49.17  522.82      50  522.89   52.33  521.41   54.22  520.83
   57.46   520.5    59.8  521.67   64.05  522.23   68.93  521.87   77.55   520.5
   82.98  518.12   91.96     514  111.04     514  117.84   518.2  119.94   519.5
  125.23  520.51  142.96     521  148.48  521.37  150.91  521.27  155.61   521.5
  170.46   530.1  181.08   533.5  183.46     534  193.09     534     200  533.37
#Mann= 8 ,-1,0
    -100     .03       0   64.05     .12       0   77.55     .06       0
   82.98     .04       0  117.84     .06       0  119.94     .12       0
  142.96     .02       0  150.91     .12       0
#XS Ineff= 3 ,-1
     -50   46.59     523      50   64.05  522.23  148.48     155  521.37
Permanent Ineff=
       F       F       F
Bank Sta=82.98,117.84
XS Rating Curve= 0 ,0
Exp/Cntr=0.3,0.1

Type RM Length L Ch R = 1 ,1000.000,14.8,17.2,20.6
XS GIS Cut Line= 3
1468731.62975802429948.2758093491468621.38432022430116.251121665
1468567.12800099 430272.39077914
#Sta/Elev= 29
    -200   524.7    -100   522.8       0  521.41   25.75  519.75   28.29  519.59
   31.05  519.65   33.37  519.28   38.85  519.01   44.11  517.86    48.2   517.5
   61.13  512.51    70.4  512.51   84.78   517.5   90.51   519.5   91.26  520.22
   98.22  520.59  106.59  521.02  108.47  521.12  118.28   525.8  127.23   530.5
  128.48     531  129.97  531.23  135.12   531.3   139.3  531.25  141.93  530.99
  143.06     531  147.37   531.5  149.35  531.59  166.35  532.05
#Mann= 9 ,-1,0
    -200    .015       0    -100     .03       0   25.75     .05       0
   44.11     .06       0    48.2     .04       0   84.78     .06       0
   90.51     .12       0   98.22     .02       0  106.59     .12       0
#XS Ineff= 1 ,-1
   27.34   30.24  519.66
Permanent Ineff=
       F
Bank Sta=48.2,84.78
XS Rating Curve= 0 ,0
Exp/Cntr=0.5,0.3