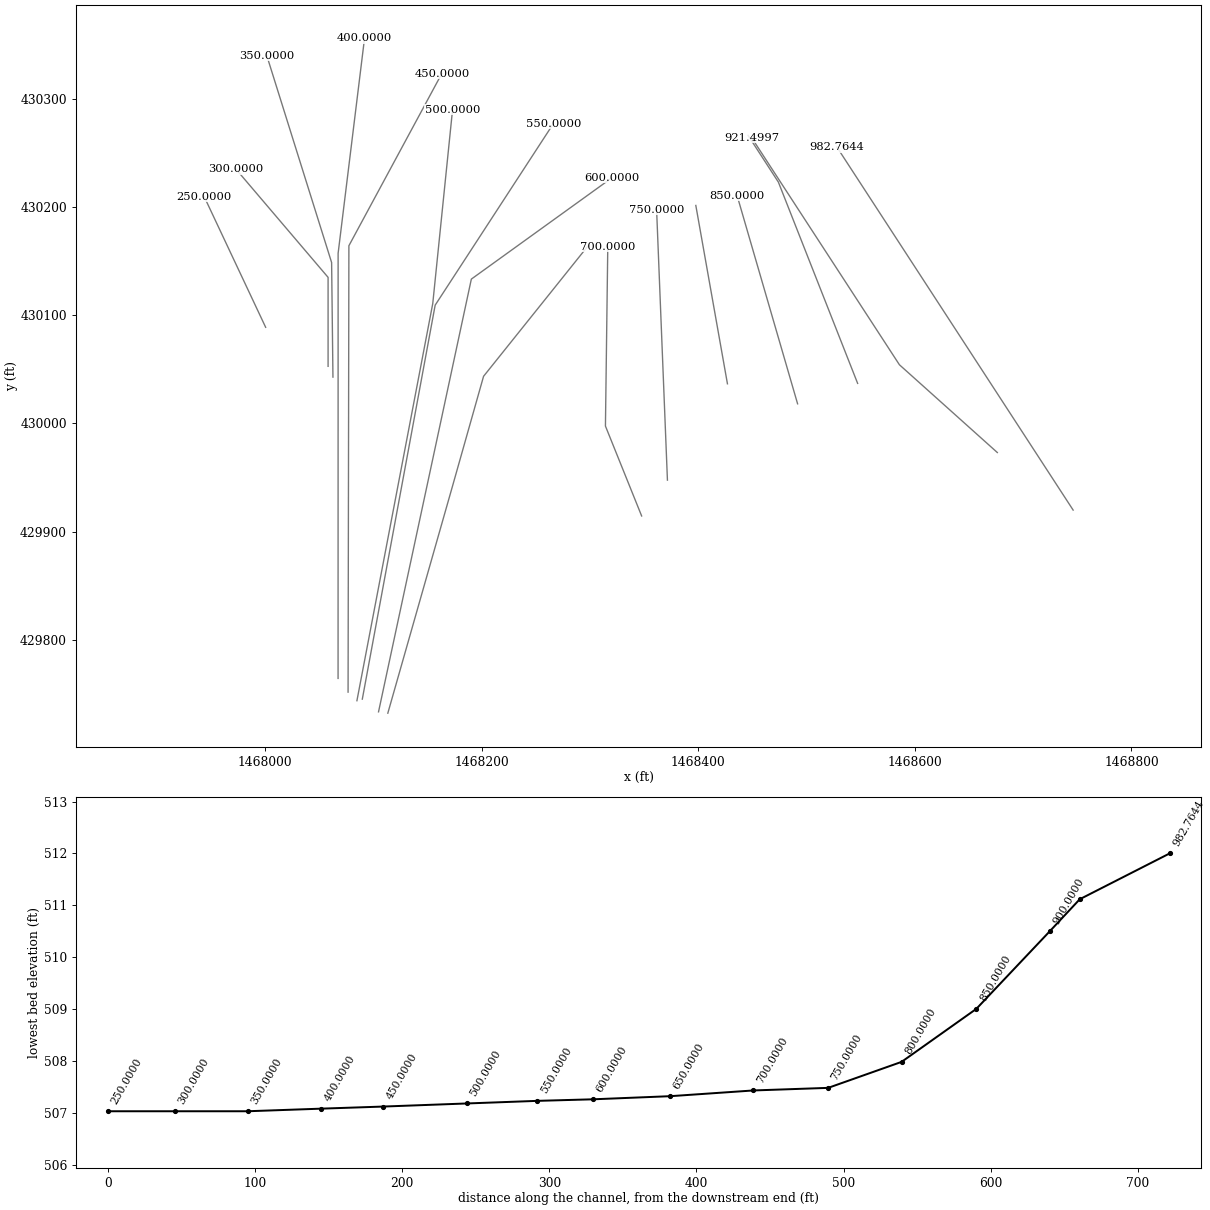
HEC-RAS study CLE-50-2.prj: CLE-50-2.25

--- CLE-50-2.g06 (geometry) --- (continued)

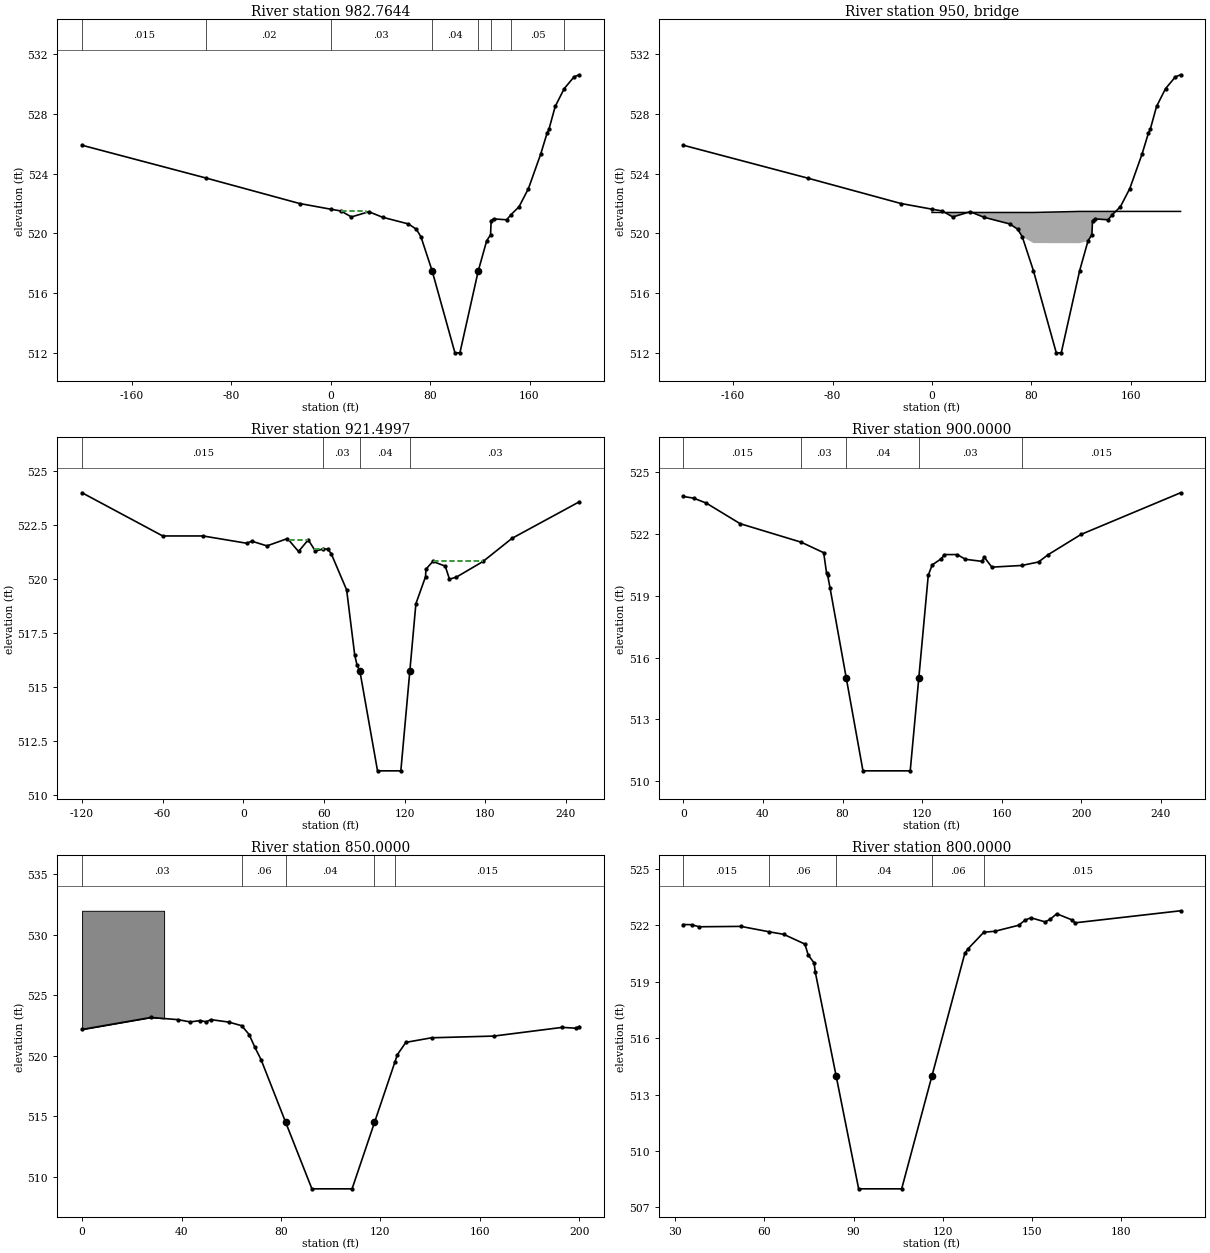
Type RM Length L Ch R = 1 ,982.7644,62.7,61,60.7
XS GIS Cut Line= 3
1468746.14501959429919.9584453481468637.05306538 430087.58584623
1468527.96111117 430255.21324711
#Sta/Elev= 30
    -200   525.9    -100   523.7     -25     522       0  521.62    8.24   521.5
   16.72   521.1   30.75  521.45   41.74  521.08   62.62  520.63   68.89  520.28
   72.61  519.78   81.62   517.5     100     512     104     512   118.8   517.5
  125.54   519.5  128.66  519.91  129.15  520.86  131.08  520.97  141.61  520.91
   145.2  521.26  151.56  521.78  159.15     523  169.09  525.33  174.16  526.72
   175.6  526.96  180.68   528.5   187.9  529.69  195.84  530.48     200  530.62
#Mann= 8 ,-1,0
    -200    .015       0    -100     .02       0       0     .03       0
   81.62     .04       0   118.8     .03       0  129.15     .02       0
   145.2     .05       0   187.9     .02       0
#XS Ineff= 1 ,-1
    8.24   28.34  521.47
Permanent Ineff=
       F
Bank Sta=81.62,118.8
XS Rating Curve= 0 ,0
Exp/Cntr=0.5,0.3

Type RM Length L Ch R = 3 ,950     ,,,
Bridge Culvert--1,0,-1,-1, 0
Deck Dist Width WeirC Skew NumUp NumDn MinLoCord MaxHiCord MaxSubmerge Is_Ogee
11.3,36,2.6,0, 4, 4, , , 0.98, 0, 0,0,,
       0   81.62   118.8     200
   521.4   521.4  521.47  521.47
  519.35  519.35  519.34  519.34
       0   86.75  123.93     200
   519.3   519.3  519.43  519.43
  517.21  517.21   517.3   517.3
BR Coef= 1 , 1 , 0 ,, 0 ,,,0.8,0,1.2,0,
WSPro=,,,, 1 ,,,, 0 ,,,, 0 ,,,,-1 ,-1 ,-1 , 0 , 0 , 0 , 0 , 0
BC Design=,, 0 ,, 0 ,,,,,,
BC Use User HTab Curves=0
BC User HTab FreeFlow(D)= 0

Type RM Length L Ch R = 1 ,921.4997,22.4,20.5,19.3
XS GIS Cut Line= 5
1468676.14883567429973.0940408371468661.25635643429986.443724806
1468585.70485838 430054.168420341468476.61290417 430221.79582122
1468449.33991562 430263.70267144
#Sta/Elev= 30
    -120     524     -60     522     -30     522    2.68  521.66    6.19  521.76
    17.6  521.54   32.87  521.88    41.1  521.28   48.31  521.82   53.66   521.3
   59.51   521.4   62.88  521.39   65.41  521.18    76.9   519.5   82.88   516.5
   84.69     516   86.75  515.74   99.89  511.12  117.24  511.12  123.93  515.74
  128.44  518.86  135.61  520.11  135.92  520.46  141.05  520.82  150.31   520.6
  153.43     520   158.5  520.09  178.45  520.82     200  521.89     250  523.58
#Mann= 4 ,-1,0
    -120    .015       0   59.51     .03       0   86.75     .04       0
  123.93     .03       0
#XS Ineff= 4 ,-1
     -30   32.87  521.88    33.9    48.2  521.82   52.48   60.36  521.41
  141.61  178.45  520.82
Permanent Ineff=
       F       F       F       F
Bank Sta=86.75,123.93
XS Rating Curve= 0 ,0
Exp/Cntr=0.5,0.3

Type RM Length L Ch R = 1 ,900.0000,49.8,49.8,49.8
XS GIS Cut Line= 3
1468547.13385365 430036.952217391468473.94643698430222.823006603
1468445.92329937430265.994281878
#Sta/Elev= 27
       0  523.82    5.07  523.74   11.47   523.5   28.52   522.5   59.24   521.6
   70.54  521.09   71.98   520.1   72.52     520   73.69   519.4    81.9     515
   90.29   510.5  114.05   510.5  118.36     515  123.13     520  125.13   520.5
  129.72   520.8  131.26     521  137.66     521  141.84  520.77  150.17  520.67
  151.24  520.88   155.1  520.39  170.07  520.47  178.57  520.64  183.51     521
     200  521.98     250     524
#Mann= 5 ,-1,0
       0    .015       0   59.24     .03       0    81.9     .04       0
  118.36     .03       0  170.07    .015       0
#XS Ineff= 1 ,-1
  137.66  183.51     521
Permanent Ineff=
       F
Bank Sta=81.9,118.36
XS Rating Curve= 0 ,0
Exp/Cntr=0.3,0.1

Type RM Length L Ch R = 1 ,850.0000,51.1,50.8,49.2
XS GIS Cut Line= 2
1468491.68972291 430018.089518641468435.89246107 430210.14853449
#Sta/Elev= 24
       0  522.19    27.7  523.18   38.51     523   43.52  522.81   47.48  522.92
   49.97  522.82   51.78     523   58.93   522.8    64.2   522.5    67.2  521.77
    69.5  520.72   72.01  519.69   81.92   514.5   92.46  509.01  108.62  509.01
  117.64   514.5  125.86   519.5  126.84   520.1  130.25  521.12  140.62   521.5
  165.62  521.64  193.18  522.36  198.69  522.29     200  522.43
#Mann= 5 ,-1,0
       0     .03       0    64.2     .06       0   81.92     .04       0
  117.64     .06       0  125.86    .015       0
#Block Obstruct= 1 ,-1
       0      33     532
Bank Sta=81.92,117.64
XS Rating Curve= 0 ,0
Exp/Cntr=0.3,0.1

Type RM Length L Ch R = 1 ,800.0000,50.5,49.9,48.5
XS GIS Cut Line= 2
1468426.90854645430036.5671496951468397.70031941  430201.2672788
#Sta/Elev= 27
   32.73  522.04   35.48  522.03   38.02  521.92   52.08  521.94   61.66  521.65
   66.44  521.52   73.61     521   74.71  520.42   76.69     520   77.11   519.5
    84.1     514   91.69  507.99  106.16  507.99  116.36     514   127.4   520.5
  128.56  520.76   133.8  521.63   137.5  521.68  145.53     522  147.65  522.27
  149.62   522.4  154.41  522.18  156.06  522.31  158.35  522.61  163.39  522.29
   164.5  522.13     200  522.77
#Mann= 5 ,-1,0
   32.73    .015       0   61.66     .06       0    84.1     .04       0
  116.36     .06       0   133.8    .015       0
Bank Sta=84.1,116.36
XS Rating Curve= 0 ,0
Exp/Cntr=0.3,0.1

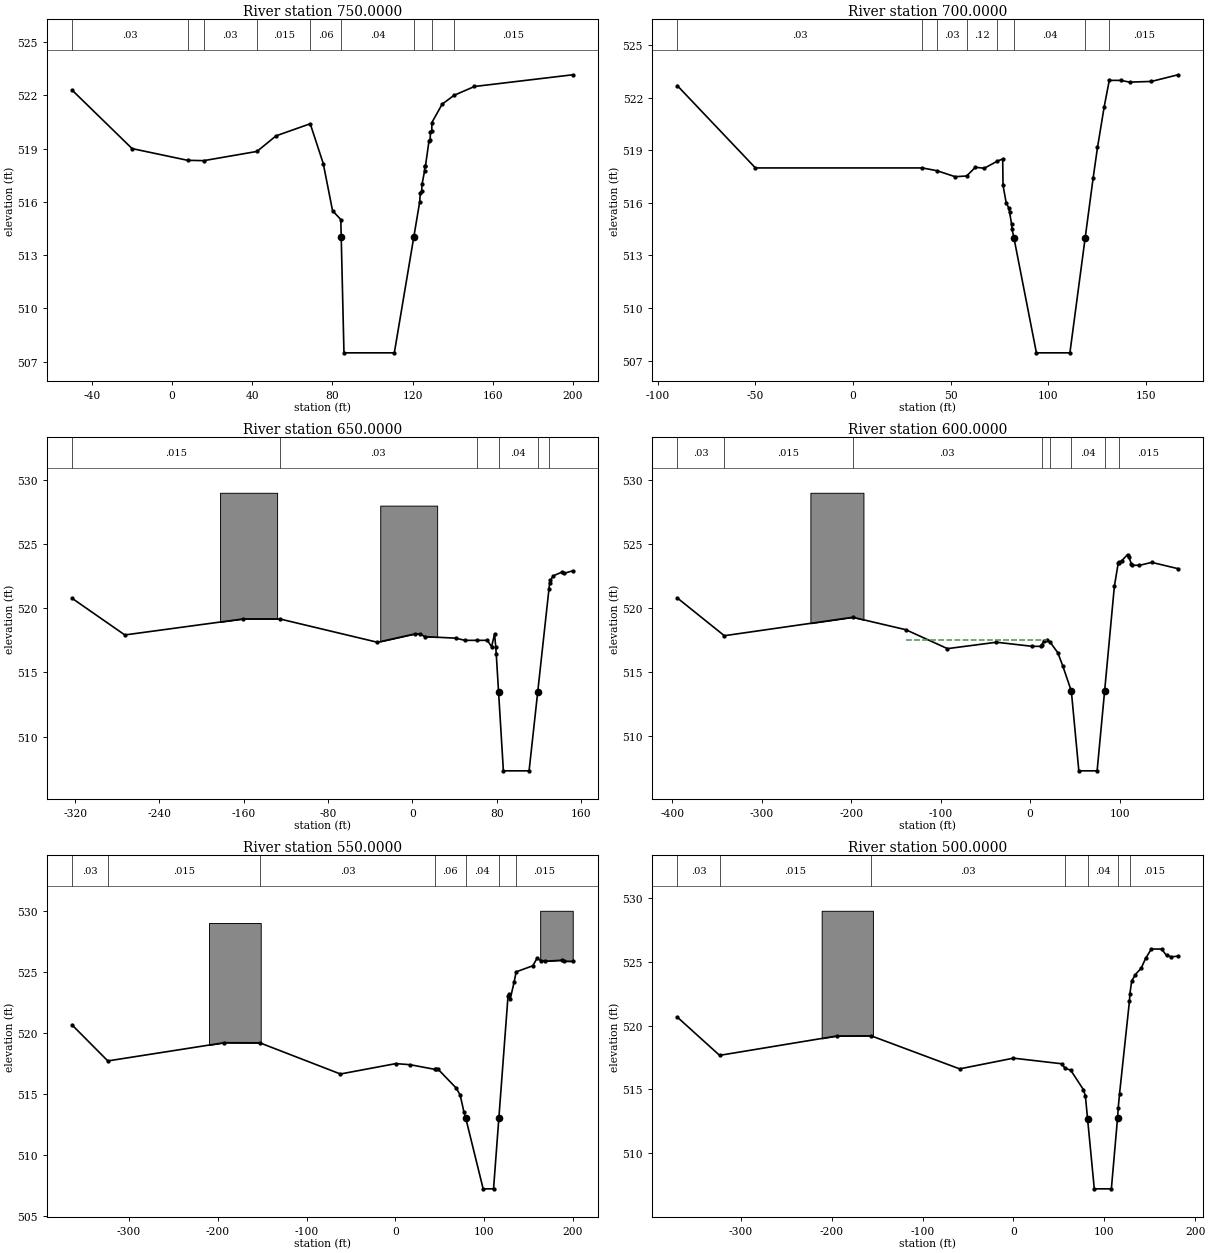
Type RM Length L Ch R = 1 ,750.0000,51,50.9,50.5
XS GIS Cut Line= 3
1468371.48612002 429947.609549891468369.48537408 429997.56950401
1468361.48239031 430197.40932049
#Sta/Elev= 30
     -50   522.3     -20     519    7.72  518.34   15.73  518.32   42.33  518.84
    51.9  519.72   68.93   520.4   75.43  518.16   80.08   515.5    84.2     515
   84.41     514   85.78  507.49  110.92  507.49  120.62     514  123.59     516
  123.88   516.5  124.56516.6009  124.78     517  126.02  517.74  126.07     518
  126.48  518.03  128.22  519.42  128.82   519.5  128.95  519.96  129.64     520
  129.68  520.47  134.78   521.5   140.7     522  150.94   522.5     200  523.16
#Mann= 9 ,-1,0
     -50     .03       0    7.72     .02       0   15.73     .03       0
   42.33    .015       0   68.93     .06       0   84.41     .04       0
  120.62     .06       0  129.68     .12       0   140.7    .015       0
Bank Sta=84.41,120.62
XS Rating Curve= 0 ,0
Exp/Cntr=0.3,0.1

Type RM Length L Ch R = 1 ,700.0000,62.2,56.4,51.2
XS GIS Cut Line= 3
1468347.67182205 429914.50974402 1468314.2359719 429997.53869117
1468316.40262427430163.201654615
#Sta/Elev= 28
     -90   522.7     -50     518   35.52     518   43.01  517.84   52.26   517.5
   58.15  517.54   62.65  518.04   67.18  517.98    73.9  518.39   76.61  518.51
   76.79     517   78.42     516   79.61  515.74   80.12   515.5   81.13   514.8
    81.4   514.5   82.38     514   93.88  507.44  111.03  507.44  118.84     514
  122.92  517.42  125.16  519.17   128.6   521.5  131.19     523  137.07     523
  141.58   522.9  152.77  522.94   166.4  523.32
#Mann= 8 ,-1,0
     -90     .03       0   35.52     .02       0   43.01     .03       0
   58.15     .12       0    73.9     .06       0   82.38     .04       0
  118.84     .06       0  131.19    .015       0
#XS Ineff= 1 ,-1
     -90   76.61  518.51
Permanent Ineff=
       F
Bank Sta=82.38,118.84
XS Rating Curve= 0 ,0
Exp/Cntr=0.3,0.1

Type RM Length L Ch R = 1 ,650.0000,54.9,52.4,51.4
XS GIS Cut Line= 4
1468113.27637661429732.4024439161468172.87876954429941.595156356
1468201.69242222 430043.499807181468297.92692726 430163.64328688
#Sta/Elev= 27
 -322.93  520.78 -272.84  517.92 -160.49  519.17 -125.99  519.17  -33.26  517.35
    2.19     518    6.97     518   11.81  517.79   40.87  517.67   49.78   517.5
   60.79   517.5   71.04   517.5   75.01     517   77.86     518   78.95     517
   79.46  516.42   81.63   513.5   86.22  507.33  110.59  507.33  118.81   513.5
  129.45   521.5  130.12     522  130.81  522.19  133.64  522.53  141.74  522.82
  144.16  522.73     152  522.92
#Mann= 6 ,-1,0
 -322.93    .015       0 -125.99     .03       0   60.79     .06       0
   81.63     .04       0  118.81     .06       0  129.45    .015       0
#XS Ineff= 2 ,-1
 -322.93 -160.49  519.17 -125.99   77.86     518
Permanent Ineff=
       F       F
#Block Obstruct= 2 ,-1
  -182.5  -128.4     529   -30.6    23.4     528
Bank Sta=81.63,118.81
XS Rating Curve= 0 ,0
Exp/Cntr=0.3,0.1

Type RM Length L Ch R = 1 ,600.0000,35,37.9,40.1
XS GIS Cut Line= 3
1468104.69286019429733.6207019661468190.40888511430133.257753229
1468320.13174031430226.751702923
#Sta/Elev= 30
 -394.33  520.78 -341.77  517.83 -198.25  519.27    -139   518.3  -92.39  516.82
  -37.61  517.32    2.39     517   11.88     517   12.79  517.12   15.51   517.4
   18.38  517.52   22.53  517.31   30.91   516.5   36.56  515.45   46.04   513.5
   54.41  507.27   74.85  507.27   83.22   513.5   94.11  521.68   98.43   523.5
   98.98  523.62   99.26  523.55  102.46   523.7  108.87  524.17  110.38     524
  113.22   523.4  114.36  523.34  122.13  523.33  135.85  523.56  165.28  523.07
#Mann= 8 ,-1,0
 -394.33     .03       0 -341.77    .015       0 -198.25     .03       0
   12.79     .12       0   22.53     .06       0   46.04     .04       0
   83.22     .06       0   98.98    .015       0
#XS Ineff= 2 ,-1
 -394.33 -198.25  519.27    -139   19.08  517.53
Permanent Ineff=
       F       F
#Block Obstruct= 1 ,-1
  -245.6  -186.3     529
Bank Sta=46.04,83.22
XS Rating Curve= 0 ,0
Exp/Cntr=0.3,0.1

Type RM Length L Ch R = 1 ,550.0000,44,47.8,51.8
XS GIS Cut Line= 3
1468089.71680587429745.3686937781468157.00660937  430109.2092995
1468266.14806495 430276.80447447
#Sta/Elev= 29
 -364.26  520.66 -323.94  517.71 -192.89   519.2 -152.56  519.19  -61.83  516.64
     .66  517.49   16.78   517.4   44.64  517.02   46.28  517.09   48.23  517.03
   68.53   515.5   73.12  514.93   77.46   513.5   79.53     513   99.04  507.24
  110.75  507.24  116.71     513  127.05     523  127.85  523.17  129.49  522.75
  133.98  524.18  136.19     525  155.02   525.5  159.66   526.1  164.15  525.92
  168.39  525.87  187.56  525.95  189.89  525.87     200  525.86
#Mann= 7 ,-1,0
 -364.26     .03       0 -323.94    .015       0 -152.56     .03       0
   44.64     .06       0   79.53     .04       0  116.71     .06       0
  136.19    .015       0
#XS Ineff= 2 ,-1
 -364.26 -192.89   519.2 -152.56     .66  517.49
Permanent Ineff=
       F       F
#Block Obstruct= 2 ,-1
  -209.9  -151.6     529   163.3     200     530
Bank Sta=79.53,116.71
XS Rating Curve= 0 ,0
Exp/Cntr=0.3,0.1

Type RM Length L Ch R = 1 ,500.0000,60.7,57.3,53.5
XS GIS Cut Line= 3
1468084.73336115429743.8986369651468154.77759391 430110.72345484
1468173.05097918430289.673024693
#Sta/Elev= 28
    -370  520.66 -323.46  517.66 -194.44  519.18 -156.57  519.19  -59.26   516.6
       0  517.44   53.15     517   56.83  516.64   62.99   516.5      77  514.97
   79.14   514.5   81.56   512.7   88.98  507.19  107.77  507.19  114.56  512.73
  115.35  513.56  116.73  514.62  127.72  521.94  128.16   522.5   130.2   523.5
  134.23     524  140.63   524.5  145.43  525.26  151.76     526     163     526
  168.47   525.5  173.81  525.39  181.16  525.44
#Mann= 7 ,-1,0
    -370     .03       0 -323.46    .015       0 -156.57     .03       0
   56.83     .06       0   81.56     .04       0  114.56     .06       0
  128.16    .015       0
#XS Ineff= 3 ,-1
                            -370 -156.57  519.19 -156.57       0  517.44
Permanent Ineff=
       F       F       F
#Block Obstruct= 1 ,-1
  -211.1  -154.7     529
Bank Sta=81.56,114.56
XS Rating Curve= 0 ,0
Exp/Cntr=0.3,0.1

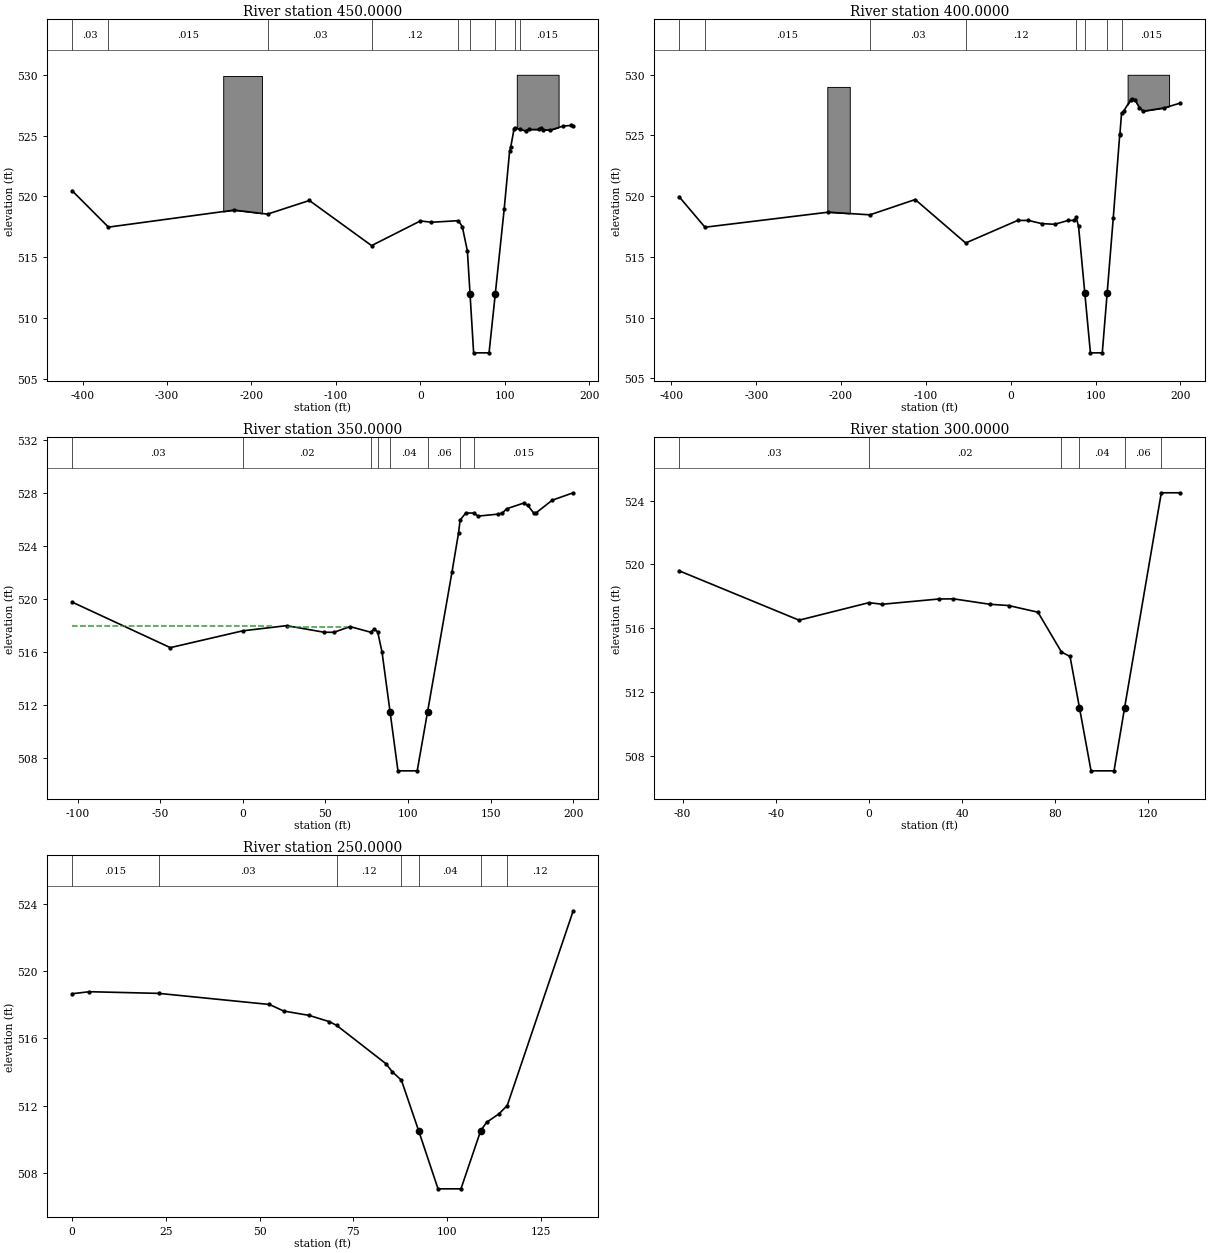
Type RM Length L Ch R = 1 ,450.0000,38.9,41.8,44.8
XS GIS Cut Line= 3
1468076.57499801429751.8331059291468077.32314336430164.061194277
1468163.15318918 430323.11235073
#Sta/Elev= 30
 -412.47  520.47 -369.37  517.47 -220.68  518.87 -181.03  518.54 -131.46  519.66
  -57.82  515.95       0  517.98    13.1  517.87   45.03     518   49.61   517.5
   55.62   515.5   58.72     512      63  507.13   81.26  507.13   88.67     512
   99.22  518.98  105.62  523.73  106.94  524.06  110.73   525.5  111.57  525.66
  118.13   525.5   124.5  525.39  128.03   525.5  140.85   525.5  142.71  525.63
  144.99  525.49   153.4  525.44  168.75  525.78  178.66  525.83  180.92  525.75
#Mann= 9 ,-1,0
 -412.47     .03       0 -369.37    .015       0 -181.03     .03       0
  -57.82     .12       0   45.03     .06       0   58.72     .04       0
   88.67     .06       0  111.57     .12       0  118.13    .015       0
#XS Ineff= 1 ,-1
 -412.47 -131.46  519.66
Permanent Ineff=
       F
#Block Obstruct= 2 ,-1
  -233.5  -187.6   529.9   114.1   163.6     530
Bank Sta=58.72,88.67
XS Rating Curve= 0 ,0
Exp/Cntr=0.3,0.1

Type RM Length L Ch R = 1 ,400.0000,46.2,50,52.5
XS GIS Cut Line= 3
1468067.33442339429764.5123954591468067.37900316 430157.09751214
1468091.76949029 430355.60470127
#Sta/Elev= 30
 -390.81  519.95 -360.39  517.44 -214.92  518.68 -165.95  518.46 -112.57  519.72
  -53.09  516.14    8.21     518    20.9     518   36.37  517.74    51.7  517.68
   67.87     518   74.76     518   77.21  518.25   80.01   517.5   87.39     512
   93.98  507.09  107.96  507.09   113.7     512   120.9   518.2  128.46     525
  128.78  525.14  130.69  526.85  133.12     527  141.65  527.96  143.14  528.03
  146.29  527.96  151.65  527.29  156.17     527  180.93  527.27     200  527.67
#Mann= 8 ,-1,0
 -390.81     .03       0 -360.39    .015       0 -165.95     .03       0
  -53.09     .12       0   77.21     .06       0   87.39     .04       0
   113.7     .06       0  130.69    .015       0
#XS Ineff= 1 ,-1
 -112.57   77.21  518.25
Permanent Ineff=
       F
#Block Obstruct= 2 ,-1
  -216.2  -189.7     529   137.8   186.7     530
Bank Sta=87.39,113.7
XS Rating Curve= 0 ,0
Exp/Cntr=0.3,0.1

Type RM Length L Ch R = 1 ,350.0000,46.7,49.3,52.2
XS GIS Cut Line= 3
1468062.59826719430042.7520125351468061.36962292  430148.5636559
1468001.57811989  430339.4169403
#Sta/Elev= 30
 -103.35  519.78  -43.86  516.34       0  517.61   26.51     518   49.31   517.5
    55.2   517.5   64.95  517.93   77.51   517.5   79.45  517.74   81.65  517.53
   84.28     516   89.13   511.5   93.91  507.04  105.56  507.04  111.84   511.5
  126.65  522.07  130.59     525  131.54  525.97  134.94   526.5  139.73   526.5
  142.45  526.27  154.61  526.42  157.14   526.5  159.63  526.82  169.97  527.25
  172.53  527.07  176.08   526.5  177.36   526.5  187.29  527.47     200  528.03
#Mann= 8 ,-1,0
 -103.35     .03       0       0     .02       0   77.51     .12       0
   81.65     .06       0   89.13     .04       0  111.84     .06       0
  131.54     .12       0  139.73    .015       0
#XS Ineff= 3 ,-1
 -103.35   18.47     518   26.51   63.37  517.91   69.67   79.45  517.74
Permanent Ineff=
       F       F       F
Bank Sta=89.13,111.84
XS Rating Curve= 0 ,0
Exp/Cntr=0.3,0.1

Type RM Length L Ch R = 1 ,300.0000,51.1,45.7,45.3
XS GIS Cut Line= 3
1468058.11406649430052.7078346611468058.11406649 430134.86339744
1467972.90442139430234.971812253
#Sta/Elev= 17
   -81.5   519.6     -30   516.5       0   517.6    5.68   517.5   29.99  517.83
   36.32  517.84   51.88   517.5   59.97  517.42    72.6     517    82.7   514.5
   86.38  514.22   90.43     511    95.4  507.04  105.27  507.04  109.81     511
  125.58   524.5  133.76   524.5
#Mann= 6 ,-1,0
   -81.5     .03       0       0     .02       0    82.7     .06       0
   90.43     .04       0  109.81     .06       0  125.58     .12       0
Bank Sta=90.43,109.81
XS Rating Curve= 0 ,0
Exp/Cntr=0.3,0.1

Type RM Length L Ch R = 1 ,250.0000,59.4,48.4,44.9
XS GIS Cut Line= 2
1468000.46513742   430088.7361661467943.77037464430209.249030465
#Sta/Elev= 19
       0  518.66    4.64  518.78   23.17  518.68   52.65  518.02   56.42  517.63
   63.21  517.37   68.56     517   70.53  516.78   83.66   514.5   85.45     514
   87.83  513.51   92.43   510.5    97.6  507.04  103.71  507.04  108.97   510.5
  110.54     511  113.81   511.5  116.05     512  133.65   523.6
#Mann= 7 ,-1,0
       0    .015       0   23.17     .03       0   70.53     .12       0
   87.83     .06       0   92.43     .04       0  108.97     .06       0
  116.05     .12       0
Bank Sta=92.43,108.97
XS Rating Curve= 0 ,0
Exp/Cntr=0.3,0.1